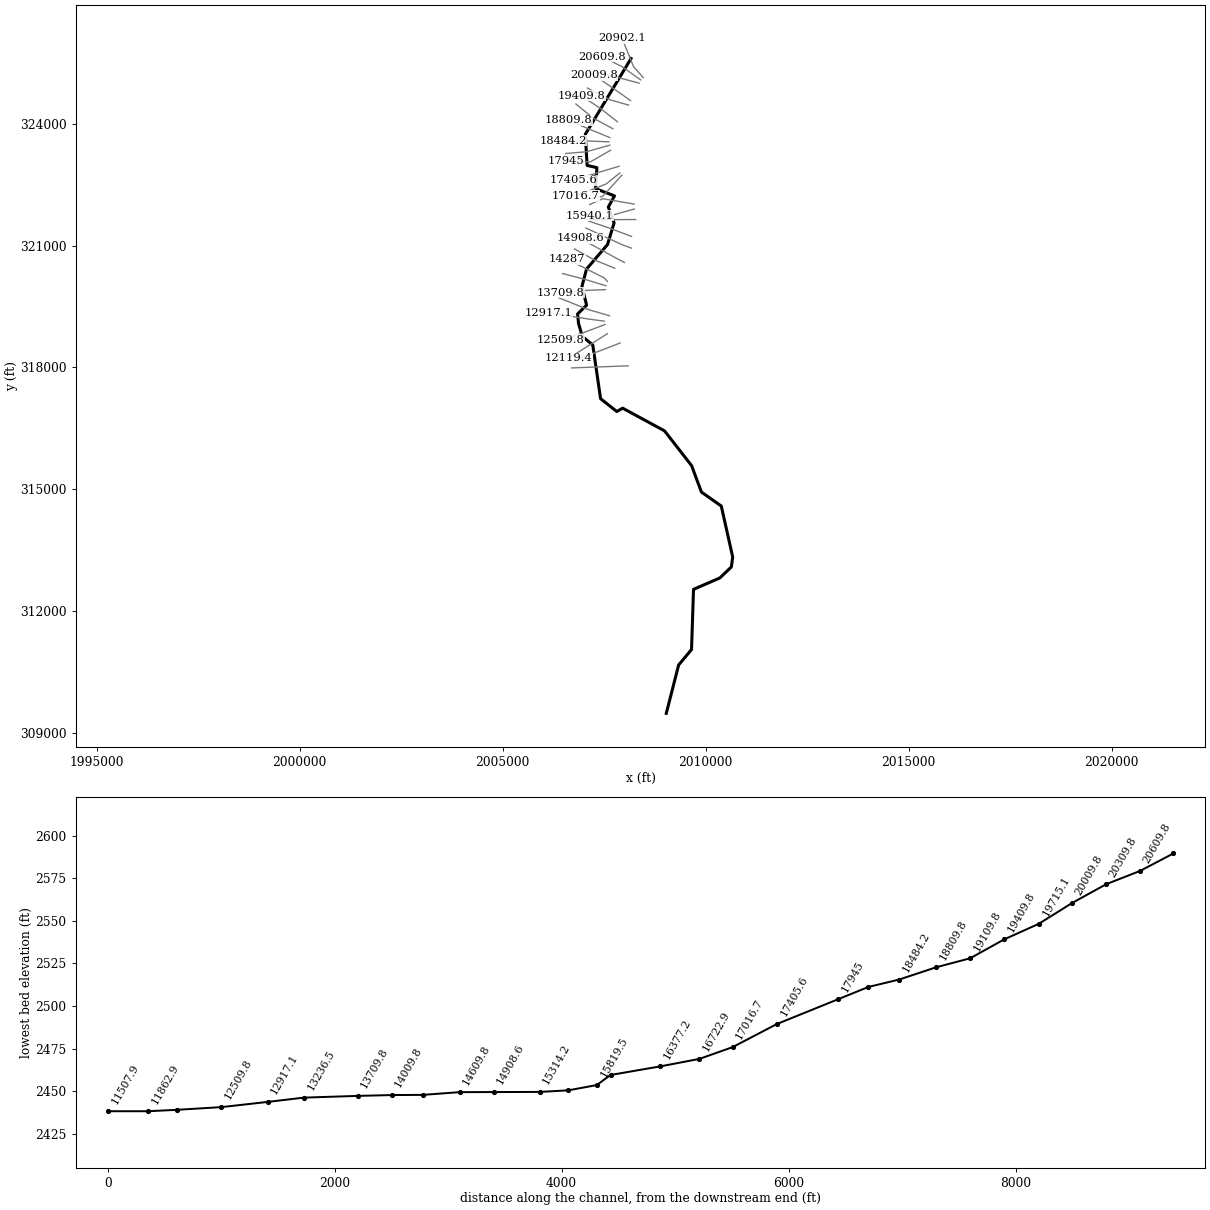
--- MeadowCrk.prj (project) ---

Proj Title=MeadowCrk
Current Plan=p01
Default Exp/Contr=0,0
English Units
Geom File=g01
Flow File=f01
Plan File=p01
BEGIN DESCRIPTION:
END DESCRIPTION:
DSS Export Rating Curves= 0
DSS Export Rating Curve Sorted= 0
DSS Export Volume Flow Curves= 0
DXF OffsetX= 0
DXF OffsetY= 0
DXF ScaleX= 0
DXF ScaleY= 0

--- MeadowCrk.p01 (plan) ---

Plan Title=Floodplain
Program Version=4.00
Geom File=g01
Flow File=f01
K Sum by GR=0
Std Step Tol=0.01
Critical Tol=0.01
Num of Std Step Trials=20
Max Error Tol=0.3
Flow Tol Ratio=0.001
Split Flow NTrial=30
Split Flow Tol=0.02
Split Flow Ratio=0.02
Log Output Level=0
Friction Slope Method=1
Unsteady Friction Slope Method=2
Unsteady Bridges Friction Slope Method=1
Global Log Level=0
CheckData=False
Run HTab=0
Run UNet=0
Run PostProcess=0
UNET Theta=0
UNET Theta Warmup=0
UNET ZTol=0
UNET ZSATol=0
UNET MxIter=0
UNET MaxInSteps=0
UNET DtIC=0
UNET DtMin=0
UNET MaxCRTS=0
UNET WFStab=0
UNET SFStab=0
UNET WFX=0
UNET SFX=0
UNET DSS MLevel=0
UNET DZMax Abort=0
UNET Convert EG Bridges=0
UNET Use Existing IB Tables=0
UNET Froude Limit=0
UNET Froude Power=0
Write IC File=0
Echo Input=False
Echo Output=False
Write Detailed=0

--- MeadowCrk.f01 (steady flow) ---

Flow Title=NFF Regression Equation
Program Version=4.00
Number of Profiles=1
Profile Names=P100yr
River Rch & RM=MeadowCrk,Main      ,20902.1
426.9552
River Rch & RM=MeadowCrk,Main      ,20609.8
551.0652
River Rch & RM=MeadowCrk,Main      ,18809.8
578.0796
River Rch & RM=MeadowCrk,Main      ,18484.2
756.2840
River Rch & RM=MeadowCrk,Main      ,16377.2
780.2278
River Rch & RM=MeadowCrk,Main      ,15940.1
867.1934
River Rch & RM=MeadowCrk,Main      ,12119.4
949.5938
River Rch & RM=MeadowCrk,Main      ,11862.9
1062.447
River Rch & RM=MeadowCrk,Main      ,11009.8
1099.621
River Rch & RM=MeadowCrk,Main      ,8250.1
1219.039
River Rch & RM=MeadowCrk,Main      ,7509.9
    1500
River Rch & RM=MeadowCrk,Main      ,6753.6
1791.466
River Rch & RM=MeadowCrk,Main      ,209.8
    2200
Boundary for River Rch & Prof#=MeadowCrk,Main      ,1
Up Type=0
Dn Type=3
Dn Slope=0.099997

--- MeadowCrk.g01 (geometry) ---

Geom Title=USGS 3m DEM
Program Version=4.10

River Reach=MeadowCrk       ,Main
Reach XY= 30
     2008161.999      325605.731     2007035.263      323737.675
     2007080.402      322973.787     2007321.722      322918.231
     2007287.486      322402.675     2007755.421      322222.885
     2007602.972      321949.481     2007745.333      321558.856
     2007583.875       321025.87     2007066.513      320421.338
     2006953.666      319996.356     2007067.517      319532.321
     2006846.532      319315.914     2006870.333      319077.953
     2006962.347      318763.717     2007219.638      318553.301
        2007412.      317230.731     2007811.364      316913.431
     2007955.402      316996.356     2008986.652      316437.328
     2009655.564       315577.99     2009895.147      314930.421
     2010384.466      314586.359      2010665.98      313329.726
     2010632.685      313086.402     2010347.945      312814.957
     2009700.702      312534.587     2009651.892      311053.131
     2009334.469      310672.592     2009029.722      309480.784

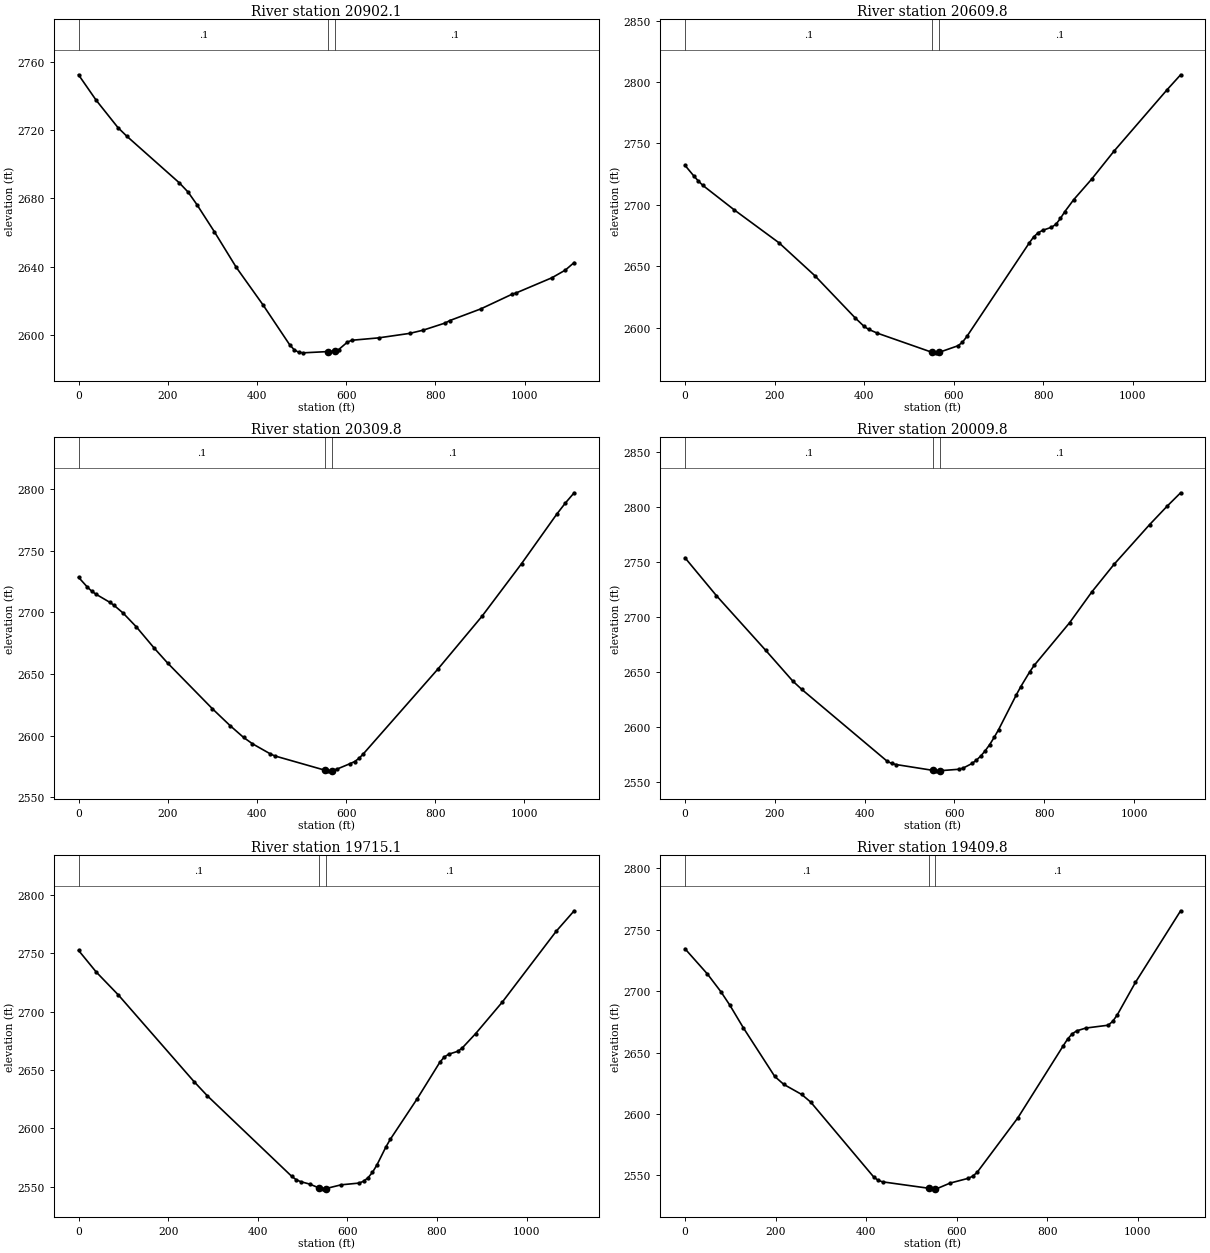
Type RM Length L Ch R = 1 ,20902.1 ,269.6,292,321
XS GIS Cut Line= 3
     2008462.264      325137.677     2008226.098      325400.957
     2007940.863      326102.754
#Sta/Elev= 30
       0 2752.31    39.3 2737.52    88.4 2721.42   108.1 2716.42     226 2689.09
   245.6 2683.71   265.3 2676.42   304.6 2660.48   353.7 2639.64   413.5 2617.74
   473.3  2594.4   483.3 2591.51   493.2 2590.01   503.2 2589.64   559.8 2590.39
   574.82590.711   582.9 2591.48   602.9 2595.92   612.8    2597   672.6 2598.39
   742.4 2601.02   772.3 2602.88   822.2  2607.1   832.1  2608.5   901.9 2615.35
   971.7  2623.9   981.6 2624.74  1061.4 2633.57  1091.3 2638.03  1111.2 2642.47
#Mann= 3 , 0 , 0
       0      .1       0   559.8    .045       0   574.8      .1       0
Bank Sta=559.8,574.8
XS Rating Curve= 0 ,0
Exp/Cntr=0.3,0.1

Type RM Length L Ch R = 1 ,20609.8 ,285.6,300.1,308.6
XS GIS Cut Line= 3
     2008400.163      325078.891     2007944.406       325403.82
     2007455.171       325648.08
#Sta/Elev= 30
       0 2732.11      20 2723.34      30 2719.27      40 2715.73     110 2695.82
   209.9 2669.02   289.9 2642.25   379.8 2607.93   399.8 2600.98   409.8 2598.57
   429.8 2595.39   552.22579.755   559.7 2579.41   567.22579.792   609.4 2585.16
   619.4    2588   629.3 2592.72   768.5 2668.84   778.4 2673.79   788.4 2677.13
   798.3 2679.14   818.2 2681.65   828.2 2684.08   838.1 2688.81     848 2694.38
   867.9 2704.15   907.7 2720.75   957.4 2743.44  1076.7 2793.79  1106.6 2805.83
#Mann= 3 , 0 , 0
       0      .1       0   552.2    .045       0   567.2      .1       0
Bank Sta=552.2,567.2
XS Rating Curve= 0 ,0
Exp/Cntr=0.3,0.1

Type RM Length L Ch R = 1 ,20309.8 ,313.7,299.8,286
XS GIS Cut Line= 3
     2008360.756      324999.035     2007819.986      325144.917
     2007285.899      325282.143
#Sta/Elev= 30
       0 2728.34      20 2720.32      30 2716.96      40 2714.44      70  2708.1
      80 2705.51     100 2699.35     130 2688.04     170 2670.85     200  2658.8
     300 2621.94   340.1 2608.13   370.1 2598.64   390.1 2593.49   430.1 2585.31
   440.1 2583.66   552.6 2572.08   560.1 2571.57   567.6 2571.79   579.8    2573
   609.3 2577.44   619.2 2579.08     629  2581.7   638.9 2585.38   806.3 2654.16
   904.8 2696.75   993.4  2739.3  1072.2 2779.32  1091.8 2788.48  1111.5 2796.76
#Mann= 3 , 0 , 0
       0      .1       0   552.6    .045       0   567.6      .1       0
Bank Sta=552.6,567.6
XS Rating Curve= 0 ,0
Exp/Cntr=0.3,0.1

Type RM Length L Ch R = 1 ,20009.8 ,289.2,294.7,299.5
XS GIS Cut Line= 3
     2008150.564      324569.524     2007693.456      324892.927
     2007244.583      325199.433
#Sta/Elev= 30
       0  2753.8      70 2719.43     180 2669.71     240 2641.98     260 2634.43
     450 2569.32     460  2567.3     470 2566.27   552.42560.965   559.9 2560.56
   567.42560.674   609.4 2561.97   619.2 2563.04     639 2567.22   648.9 2570.27
   658.8 2574.13   668.6 2578.86   678.5 2584.43   688.4 2590.91   698.3 2597.99
   737.8 2629.58   747.7 2636.97   767.5 2650.32   777.4 2656.16   856.4 2694.93
   905.8 2722.82   955.2  2747.8  1034.3  2783.8  1073.8 2800.72  1103.5 2812.72
#Mann= 3 , 0 , 0
       0      .1       0   552.4    .045       0   567.4      .1       0
Bank Sta=552.4,567.4
XS Rating Curve= 0 ,0
Exp/Cntr=0.3,0.1

Type RM Length L Ch R = 1 ,19715.1 ,312.6,305.2,301.3
XS GIS Cut Line= 3
     2008103.711      324458.367     2007646.185      324589.555
     2007086.603      324878.978
#Sta/Elev= 30
       0 2752.49    39.7 2733.85    89.2 2714.17   257.8 2640.09   287.6  2627.9
     476  2558.9     486 2556.04     496 2554.41     516 2552.34   536.72549.043
     546 2548.29   551.72548.495     586 2551.73     626 2553.22     636  2554.8
     646 2557.77     656 2562.45     666 2568.81     686 2584.24     696 2590.86
     756 2625.58     806 2656.51     816 2661.13     826 2663.54     846 2666.01
     856 2668.79     886 2681.13     946 2708.35    1066 2768.86    1106 2786.36
#Mann= 3 , 0 , 0
       0      .1       0   536.7    .045       0   551.7      .1       0
Bank Sta=536.7,551.7
XS Rating Curve= 0 ,0
Exp/Cntr=0.3,0.1

Type RM Length L Ch R = 1 ,19409.8 ,292.9,300,295.6
XS GIS Cut Line= 3
     2007825.873      324048.651     2007397.346      324386.035
     2006937.286      324685.936
#Sta/Elev= 30
       0  2734.4    49.6 2713.85    79.3 2699.47    99.2 2688.43   128.9  2670.1
   198.3 2630.52   218.2 2624.08   257.8 2615.88   277.7 2609.69   416.5 2548.92
   426.4 2546.09   436.3 2544.83   537.92539.632   552.92539.147   555.4 2539.14
   585.3 2543.79   625.3 2547.67   635.3 2549.37   645.2 2552.56   735.1 2596.87
     835 2655.28     845 2660.96   854.9 2665.13   864.9 2667.59   884.9 2669.88
   934.8 2672.23   944.8 2675.46   954.8 2680.69   994.7 2706.99  1094.6 2765.28
#Mann= 3 , 0 , 0
       0      .1       0   537.9    .045       0   552.9      .1       0
Bank Sta=537.9,552.9
XS Rating Curve= 0 ,0
Exp/Cntr=0.3,0.1

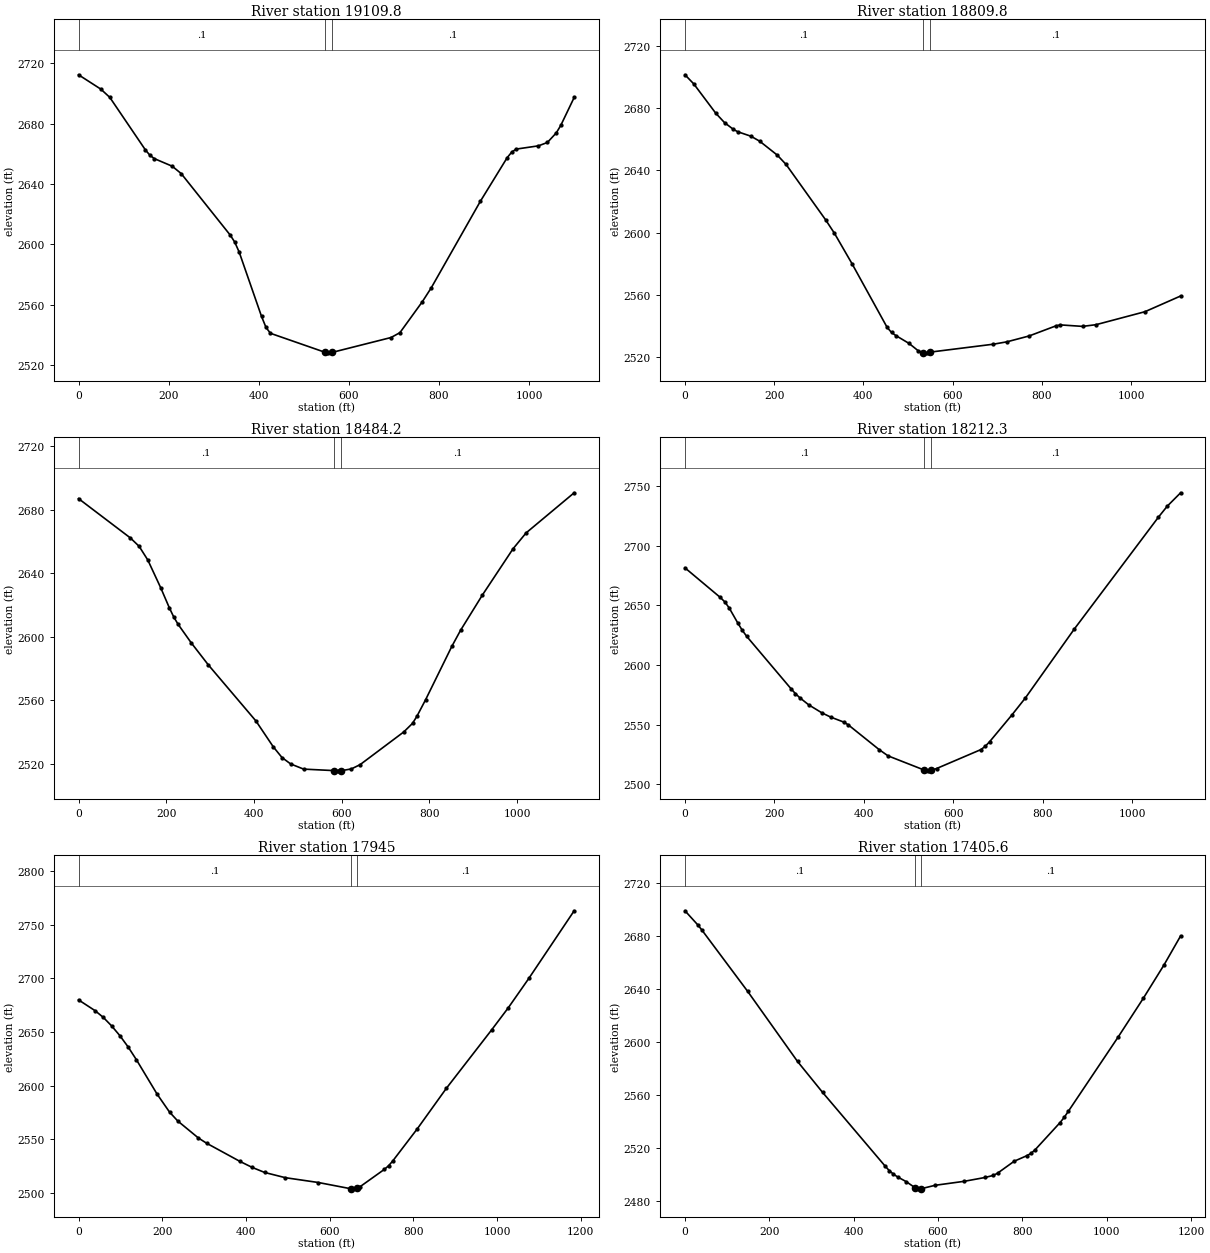
Type RM Length L Ch R = 1 ,19109.8 ,296.1,300,311.2
XS GIS Cut Line= 3
     2007715.204      323876.951     2007227.111      324140.686
     2006804.972       324485.85
#Sta/Elev= 30
       0 2712.38    49.5 2702.87    69.4 2697.41   148.6 2662.51   158.5 2659.01
   168.4 2656.78     208 2651.76   227.9 2646.88   336.8 2606.07   346.7 2601.48
   356.6 2594.84   406.2  2552.2   416.1  2544.9     426 2540.99   547.32528.388
   554.8 2528.04   562.3 2528.29   693.6 2538.19   713.4 2541.42     763 2561.89
   782.8 2571.09   891.9 2628.51   951.4 2657.42   961.3 2661.05   971.2  2663.1
  1020.8 2665.27  1040.6 2667.49  1060.4 2673.85  1070.3 2678.77  1100.1 2697.33
#Mann= 3 , 0 , 0
       0      .1       0   547.3    .045       0   562.3      .1       0
Bank Sta=547.3,562.3
XS Rating Curve= 0 ,0
Exp/Cntr=0.3,0.1

Type RM Length L Ch R = 1 ,18809.8 ,312.1,325.7,341.6
XS GIS Cut Line= 3
     2007638.283      323659.186     2007137.224      323865.504
     2006613.544      324089.017
#Sta/Elev= 30
       0 2701.36    19.7 2695.51      69 2676.68    88.7 2670.62   108.4 2666.32
   118.2 2664.78   147.8  2661.9   167.5  2658.7   206.9 2649.77   226.6 2643.78
   315.3  2608.2     335  2599.6   374.4 2580.06   453.2 2539.12   463.1 2535.82
   472.9 2533.83   502.5 2528.78   522.2 2524.25   534.4 2522.78   541.9 2522.75
   549.4  2523.2   691.7 2528.31   721.7 2529.82   771.6 2533.59   831.6 2540.07
   841.6  2540.7   891.5 2539.74   921.5 2540.83  1031.3 2549.17  1111.3 2559.27
#Mann= 3 , 0 , 0
       0      .1       0   534.4    .045       0   549.4      .1       0
Bank Sta=534.4,549.4
XS Rating Curve= 0 ,0
Exp/Cntr=0.3,0.1

Type RM Length L Ch R = 1 ,18484.2 ,258.7,271.8,283.1
XS GIS Cut Line= 3
     2007617.656      323553.595      2007026.04      323578.886
     2006488.185      323578.886
#Sta/Elev= 30
       0 2687.04   118.4 2662.22   138.2 2656.98   157.9 2648.39   187.5 2630.82
   207.2 2618.16   217.1 2612.48     227 2607.87   256.6 2596.33   296.1 2582.24
   404.6 2546.93   444.1 2530.66   463.9 2523.94   483.6 2519.91   513.2 2516.65
   582.72515.704   592.2 2515.56   597.72515.594     622 2516.76     642 2519.46
   741.6 2540.08   761.5 2545.48   771.4 2549.88   791.4 2560.41   851.1 2593.96
     871 2604.08   920.8 2626.31   990.6 2655.41  1020.4 2665.42    1130  2690.7
#Mann= 3 , 0 , 0
       0      .1       0   582.7    .045       0   597.7      .1       0
Bank Sta=582.7,597.7
XS Rating Curve= 0 ,0
Exp/Cntr=0.3,0.1

Type RM Length L Ch R = 1 ,18212.3 ,279.2,267.3,255.3
XS GIS Cut Line= 3
     2007638.999      323472.005     2007059.111       323309.21
     2006554.677      323266.953
#Sta/Elev= 30
       0 2681.36      79 2656.55    88.9  2652.9    98.7 2647.87   118.5 2634.86
   128.4 2628.88   138.2 2623.87     237 2580.09   246.8 2576.01   256.7 2572.51
   276.5 2566.58   306.1 2559.82   325.8 2556.26   355.5 2552.01   365.3 2549.72
   434.4 2528.95   454.2 2523.74   535.12511.836   543.1 2511.19   550.12511.511
   562.8 2513.14   661.9 2529.02   671.8 2531.85   681.7 2535.77   731.3 2558.11
   761.1  2572.2   870.3 2629.87  1058.9  2723.9  1078.7 2733.13  1108.5 2744.31
#Mann= 3 , 0 , 0
       0      .1       0   535.1    .045       0   550.1      .1       0
Bank Sta=535.1,550.1
XS Rating Curve= 0 ,0
Exp/Cntr=0.3,0.1

Type RM Length L Ch R = 1 ,17945   ,526.8,539.2,551.5
XS GIS Cut Line= 3
     2007660.547      323348.395     2007164.116       323062.21
      2006553.18      323076.102
#Sta/Elev= 30
       0 2679.94    39.5  2669.9    59.3  2663.6      79 2655.75    98.8 2646.61
   118.6 2636.08   138.3  2624.2   187.7  2592.2   217.4 2575.47   237.1 2567.13
   286.5 2551.28   306.3 2546.37   385.3 2529.58   414.9 2523.92   444.6 2519.22
     494 2514.35     573 2509.86   649.92504.091   651.9 2503.96   664.92504.621
   671.6 2505.67   730.7  2522.1   740.6  2525.4   750.4 2529.77   809.6    2560
   878.6 2597.48     987 2652.02  1026.4 2672.41  1075.7 2699.87  1184.1 2762.91
#Mann= 3 , 0 , 0
       0      .1       0   649.9    .045       0   664.9      .1       0
Bank Sta=649.9,664.9
XS Rating Curve= 0 ,0
Exp/Cntr=0.3,0.1

Type RM Length L Ch R = 1 ,17405.6 ,385.2,388.9,391.7
XS GIS Cut Line= 3
     2007867.326      322952.213     2007336.638      322793.651
     2006744.269       322604.94
#Sta/Elev= 30
       0  2699.3    29.7 2688.89    39.6 2684.98   148.4 2638.59     267 2585.54
   326.4 2562.21   474.8 2506.54   484.6 2503.15   494.5 2500.49   504.4 2498.37
   524.2 2494.94   545.7 2490.28   553.9 2489.41   560.72489.542   593.3 2492.08
   662.4  2495.1   711.8 2497.99   731.5 2499.58   741.4 2501.22   780.8 2510.24
   810.4 2514.37   820.3 2516.12   830.2 2518.81   889.4 2539.33   899.3 2543.29
   909.1 2547.86  1027.6  2604.1  1086.8  2633.1  1136.1 2658.38  1175.6 2680.34
#Mann= 3 , 0 , 0
       0      .1       0   545.7    .045       0   560.7      .1       0
Bank Sta=545.7,560.7
XS Rating Curve= 0 ,0
Exp/Cntr=0.3,0.1

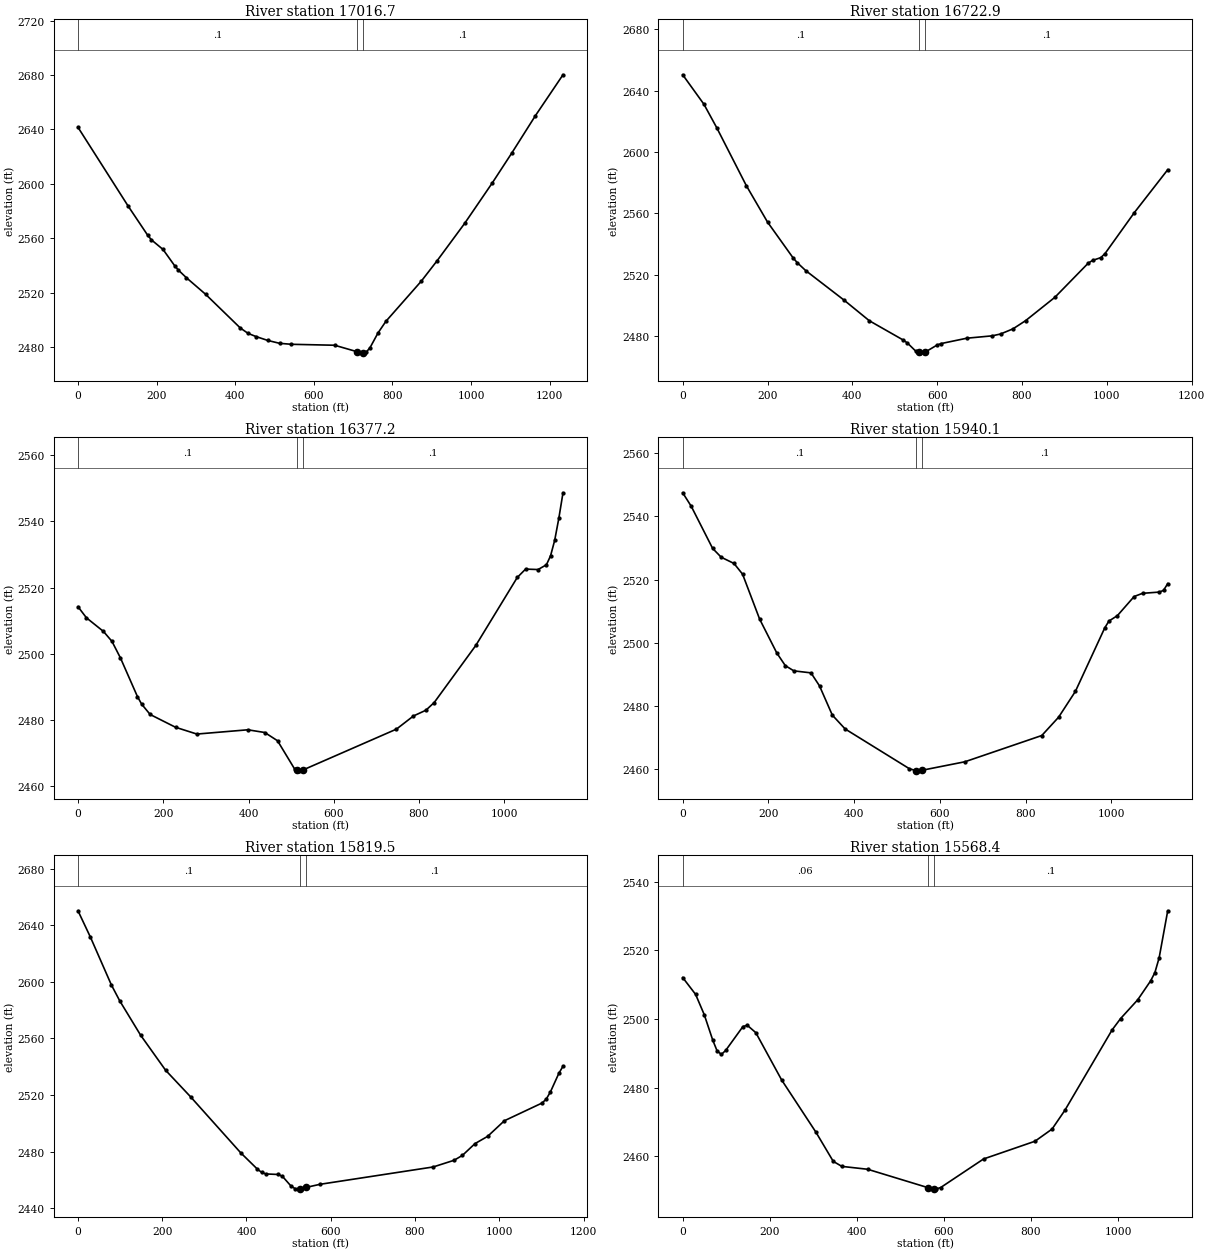
Type RM Length L Ch R = 1 ,17016.7 ,275.1,293.6,311
XS GIS Cut Line= 3
     2007885.783      322787.344     2007548.339      322516.602
     2006804.166       322219.99
#Sta/Elev= 30
       0 2641.61   127.8 2583.63     177 2562.42   186.8 2558.89   216.3 2551.85
   245.8 2539.94   255.6 2536.62   275.3 2531.19   324.5 2518.93     413  2494.1
   432.6 2490.18   452.7 2487.85   482.7 2484.98   512.7 2482.87   542.8 2482.15
   652.9 2481.45   709.3 2476.75     723 2475.87   724.32475.923     733 2476.28
   743.1 2479.79   763.1 2490.45   783.1 2498.98   873.2 2528.52   913.3 2543.48
   983.4 2570.94  1053.5 2600.59  1103.6 2622.77  1163.6 2650.19  1233.7 2680.21
#Mann= 3 , 0 , 0
       0      .1       0   709.3    .045       0   724.3      .1       0
Bank Sta=709.3,724.3
XS Rating Curve= 0 ,0
Exp/Cntr=0.3,0.1

Type RM Length L Ch R = 1 ,16722.9 ,383.6,345.7,308.1
XS GIS Cut Line= 3
     2007936.525      322733.285     2007458.548      322208.448
     2007030.175      322141.627
#Sta/Elev= 30
       0 2650.33      50 2631.13      80 2615.92     150 2578.01     200 2554.24
     260 2530.98     270 2527.77     290  2522.6   379.9 2503.44   439.9  2489.9
   519.9  2477.3   529.9 2475.33   549.9 2469.92     5572469.231   559.9 2468.95
     5722469.489   599.9 2474.07   609.9 2475.04   669.9  2478.5   729.6 2480.04
   749.3 2481.24   778.8 2484.62   808.4 2489.95   877.4 2505.18   956.2  2527.5
   966.1 2529.22   985.8 2531.08   995.6 2533.71  1064.6 2560.39  1143.4  2588.4
#Mann= 3 , 0 , 0
       0      .1       0     557    .045       0     572      .1       0
Bank Sta=557,572
XS Rating Curve= 0 ,0
Exp/Cntr=0.3,0.1

Type RM Length L Ch R = 1 ,16377.2 ,420.1,437,453.8
XS GIS Cut Line= 3
     2008239.071      322021.788     2007463.321      322153.559
     2007143.533      322009.177
#Sta/Elev= 30
       0 2514.21    19.9 2510.84    59.8 2506.72    79.7 2503.72    99.6 2498.71
   139.4 2487.03   149.4 2484.71   169.3 2481.59   229.1 2477.71   278.9 2475.67
   398.4 2476.96   438.2 2476.14   468.1 2473.64     508 2465.13   513.52464.802
   517.9 2464.54   528.52464.845     747 2477.16   786.9 2481.14   816.1 2482.88
   835.6 2485.21   933.1 2502.47  1030.5 2523.07    1050 2525.59  1079.2 2525.45
  1098.8 2526.89  1108.5  2529.6  1118.2 2534.28    1128 2541.02  1137.7 2548.68
#Mann= 3 , 0 , 0
       0      .1       0   513.5    .045       0   528.5      .1       0
Bank Sta=513.5,528.5
XS Rating Curve= 0 ,0
Exp/Cntr=0.3,0.1

Type RM Length L Ch R = 1 ,15940.1 ,130.7,120.6,110.4
XS GIS Cut Line= 3
     2008241.531      321900.053     2007435.118      321673.439
     2007147.061      321730.408
#Sta/Elev= 30
       0 2547.49    19.9 2543.22    69.8 2529.89    89.8  2527.1   119.7 2525.12
   139.6 2521.75   179.5  2507.5   219.4 2496.82   239.3  2492.8   259.3 2491.14
   299.2 2490.51   319.1 2486.39     349 2477.14   378.9 2472.76   528.5  2460.2
   544.32459.552   548.5 2459.51   559.3 2459.72   658.2 2462.38   837.6 2470.69
   876.8 2476.48     916 2484.66   984.5 2504.76   994.2 2506.91  1013.8  2508.6
    1053 2514.67  1072.6 2515.68  1111.7 2516.07  1121.5 2516.62  1131.3 2518.74
#Mann= 3 , 0 , 0
       0      .1       0   544.3    .045       0   559.3      .1       0
Bank Sta=544.3,559.3
XS Rating Curve= 0 ,0
Exp/Cntr=0.3,0.1

Type RM Length L Ch R = 1 ,15819.5 ,265.8,251.1,237.6
XS GIS Cut Line= 3
     2008275.089        321641.2     2007740.125      321637.765
     2007123.831      321634.978
#Sta/Elev= 30
       0 2650.39    29.7 2631.63    79.3  2597.9    99.1 2586.65   148.6 2562.37
     208 2537.52   267.5 2518.66   386.4 2479.06     426  2467.5   435.9 2465.26
   445.8 2464.14   475.5 2463.75   485.4 2462.41   505.2 2455.71   515.2 2453.73
   525.1 2453.59   526.6 2453.67   541.62454.614   574.7 2456.81   843.1 2469.07
   892.8 2473.81   912.7 2477.31   942.5 2485.62   972.4 2490.73  1012.1 2501.77
  1101.6 2514.33  1111.5  2517.1  1121.4 2522.15  1141.3 2535.23  1151.3 2540.39
#Mann= 3 , 0 , 0
       0      .1       0   526.6    .045       0   541.6      .1       0
Bank Sta=526.6,541.6
XS Rating Curve= 0 ,0
Exp/Cntr=0.3,0.1

Type RM Length L Ch R = 1 ,15568.4 ,260.3,253.9,248.3
XS GIS Cut Line= 3
     2008173.625      321224.766     2007646.904      321424.331
     2007125.083      321601.407
#Sta/Elev= 30
       0 2512.03    29.6 2507.14    49.4 2501.26    69.2 2493.75      79 2490.68
    88.9 2489.65    98.8 2490.82   138.3 2497.75   148.2 2498.15     168 2495.98
   227.3 2482.21   306.3 2466.95   345.9  2458.5   365.6 2457.04   424.9  2456.2
     5632450.864     578 2450.52   582.9  2450.5   592.8 2450.89   691.2  2459.2
   809.3 2464.36   848.6 2467.91   878.1 2473.39   986.4 2496.76  1006.1  2500.1
  1045.4 2505.56    1075 2511.06  1084.8 2513.47  1094.6 2517.78  1114.3 2531.48
#Mann= 3 , 0 , 0
       0     .06       0     563    .045       0     578      .1       0
Bank Sta=563,578
XS Rating Curve= 0 ,0
Exp/Cntr=0.3,0.1

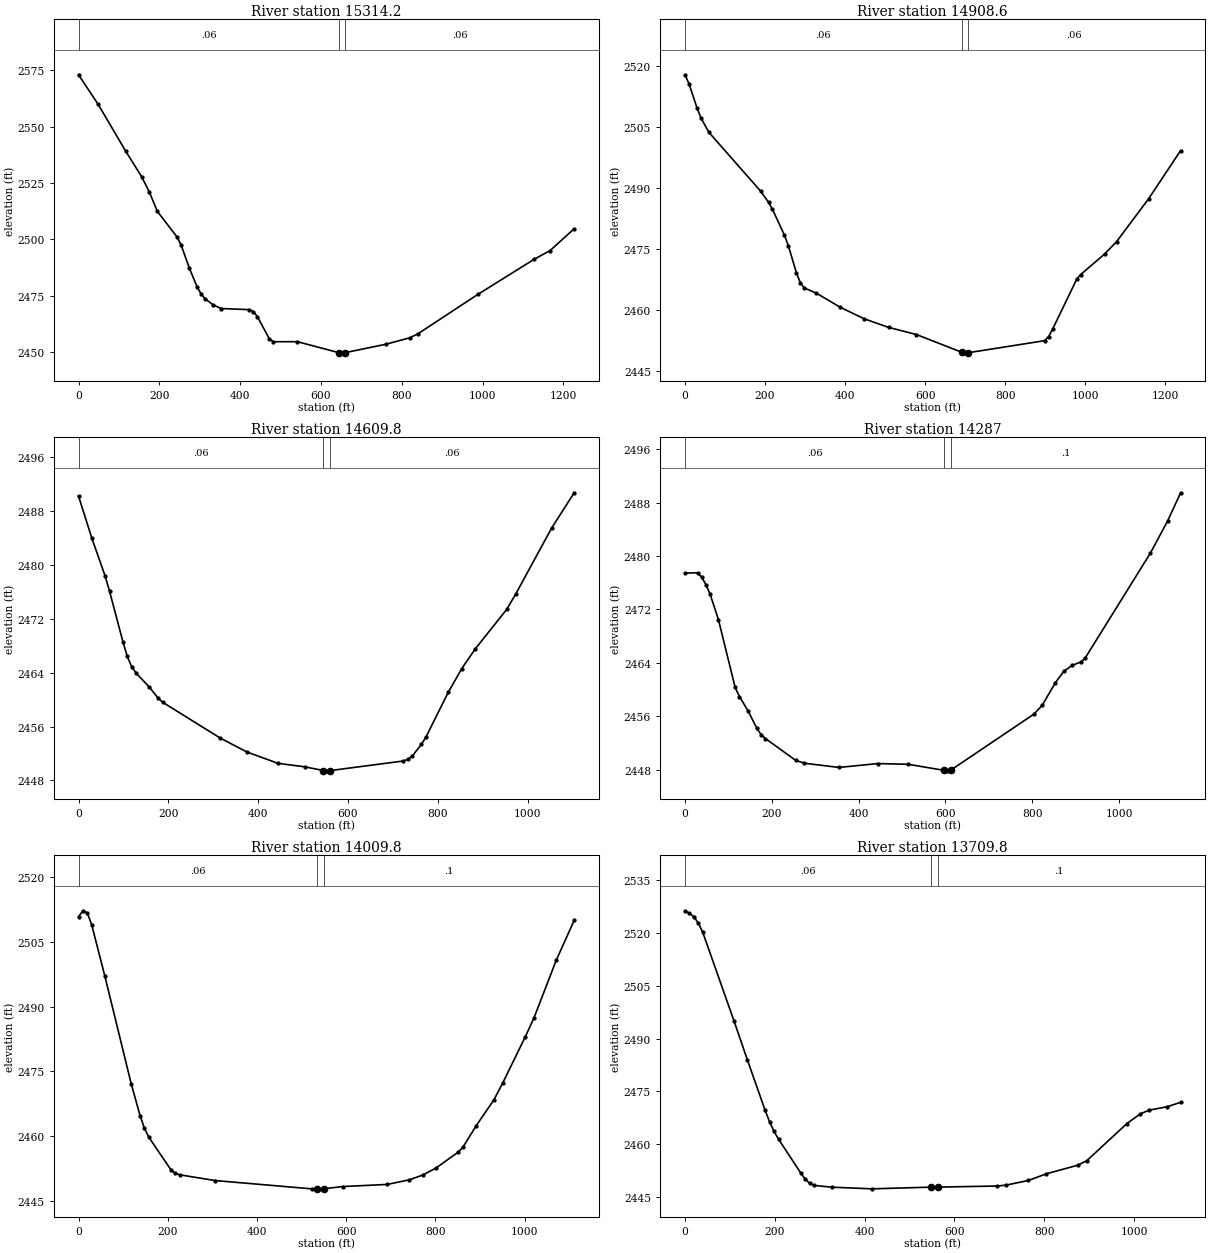
Type RM Length L Ch R = 1 ,15314.2 ,405,405.4,403.9
XS GIS Cut Line= 3
     2008174.203      320936.844     2007972.148      321008.438
     2007052.709      321431.425
#Sta/Elev= 30
       0    2573    48.7 2559.85   116.9 2539.04   155.9 2527.84   175.4  2520.9
   194.9 2512.41   244.1 2500.91     254 2497.35   273.9 2487.35   293.7  2478.7
   303.7  2475.6   313.6 2473.52   333.4  2470.8   353.3 2469.22   422.7 2468.74
   432.6 2467.91   442.6 2465.64   472.3 2455.74   482.3  2454.5   541.8 2454.51
   643.82449.646   650.9 2449.56   658.82449.615   760.1 2453.36   819.6 2456.23
   839.5 2457.97   988.3 2475.53  1127.2 2491.08  1166.9 2494.97  1226.4 2504.65
#Mann= 3 , 0 , 0
       0     .06       0   643.8    .045       0   658.8     .06       0
Bank Sta=643.8,658.8
XS Rating Curve= 0 ,0
Exp/Cntr=0.3,0.1

Type RM Length L Ch R = 1 ,14908.6 ,294.2,298.7,298.5
XS GIS Cut Line= 3
     2007997.494      320584.053     2007795.439      320690.649
     2006910.404      321176.089
#Sta/Elev= 30
       0 2517.88     9.9  2515.7    29.8 2509.81    39.7  2507.3    59.6 2503.74
   188.7 2489.28   208.6 2486.52   218.5 2484.78   248.4 2478.42   258.4 2475.77
   278.4 2469.12   288.4 2466.66   298.4 2465.42   328.4 2464.14   388.4 2460.66
   448.3 2457.83   508.3 2455.75   578.2 2453.98   690.92449.633   698.2 2449.48
   705.92449.488   898.1 2452.47   908.1 2453.48   918.1 2455.29     978 2467.53
     988 2468.72    1048 2473.78    1078 2476.84  1157.9 2487.38  1237.9 2499.24
#Mann= 3 , 0 , 0
       0     .06       0   690.9    .045       0   705.9     .06       0
Bank Sta=690.9,705.9
XS Rating Curve= 0 ,0
Exp/Cntr=0.3,0.1

Type RM Length L Ch R = 1 ,14609.8 ,327.3,322.9,324.3
XS GIS Cut Line= 3
     2007763.354      320441.097     2007251.383      320650.281
     2006769.786      320917.616
#Sta/Elev= 30
       0 2490.21    29.6 2483.98    59.3 2478.34    69.1 2476.09    98.8 2468.62
   108.6 2466.41   118.5 2464.88   128.4 2463.93     158 2461.84   177.8 2460.18
   187.6  2459.6     316 2454.28   375.3 2452.22   444.4 2450.54   503.7 2450.03
   545.62449.475   553.1 2449.43   560.62449.468   723.3 2450.89   733.3 2451.12
   743.3 2451.62   763.4 2453.34   773.4 2454.39   823.5 2461.09   853.5  2464.6
   883.6 2467.53   953.6 2473.39   973.7 2475.67  1053.8 2485.47  1103.9  2490.7
#Mann= 3 , 0 , 0
       0     .06       0   545.6    .045       0   560.6     .06       0
Bank Sta=545.6,560.6
XS Rating Curve= 0 ,0
Exp/Cntr=0.3,0.1

Type RM Length L Ch R = 1 ,14287   ,266.2,277,286.3
XS GIS Cut Line= 3
     2007581.285      320116.876     2007503.856      320202.662
     2006588.041      320665.514
#Sta/Elev= 30
       0 2477.46    28.9 2477.49    38.5 2476.84    48.2 2475.72    57.8 2474.31
      77 2470.49   115.6 2460.32   125.5 2458.95   145.4  2456.8   165.4 2454.22
   175.3 2453.25   185.3 2452.67     255  2449.4     275 2448.97   354.7 2448.34
   444.3 2448.92   514.1 2448.81   597.22447.902   603.7 2447.83   612.22447.932
     803 2456.29   822.9 2457.64   852.8    2461   872.7 2462.75   892.6 2463.65
   912.6 2464.15   922.5  2464.8    1072 2480.44  1111.8 2485.27  1141.7 2489.48
#Mann= 3 , 0 , 0
       0     .06       0   597.2    .045       0   612.2      .1       0
Bank Sta=597.2,612.2
XS Rating Curve= 0 ,0
Exp/Cntr=0.3,0.1

Type RM Length L Ch R = 1 ,14009.8 ,286.3,299.9,314.6
XS GIS Cut Line= 3
     2007545.359      320010.313     2007026.387      320167.742
      2006475.96      320311.295
#Sta/Elev= 30
       0 2510.85     9.9 2512.23    19.7 2511.75    29.6 2508.96    59.2 2497.01
   118.3 2472.02     138 2464.71   147.9 2461.73   157.8 2459.67   207.1 2452.15
   216.9 2451.31   226.8 2450.98   305.7 2449.65   522.6 2447.72   534.8 2447.72
   549.82447.735   592.2 2448.25     692 2448.74   741.9 2449.82   771.9 2450.93
   801.8 2452.57   851.7 2456.28   861.7 2457.37   891.6 2462.37   931.5 2468.41
   951.5 2472.38  1001.4 2482.94  1021.4 2487.46  1071.2  2500.8  1111.2 2509.99
#Mann= 3 , 0 , 0
       0     .06       0   534.8    .045       0   549.8      .1       0
Bank Sta=534.8,549.8
XS Rating Curve= 0 ,0
Exp/Cntr=0.3,0.1

Type RM Length L Ch R = 1 ,13709.8 ,489.9,473.1,454
XS GIS Cut Line= 3
     2007531.482      319914.704     2006976.236      319893.208
     2006430.818      319837.262
#Sta/Elev= 30
       0 2526.38     9.9  2525.7    19.8 2524.67    29.8 2522.86    39.7 2520.21
   109.2 2495.03   138.9 2483.96   178.6 2469.54   188.5 2466.28   198.4 2463.57
   208.4 2461.36     258 2451.71   267.9 2449.98   277.8 2448.77   287.8  2448.2
   327.4  2447.7   416.8 2447.23   548.22447.712   563.22447.728   695.2 2448.03
   715.2 2448.29     765 2449.62   804.9 2451.51   874.7 2453.96   894.6 2455.21
   984.3 2465.82  1014.2 2468.58  1034.2 2469.64    1074  2470.6  1103.9 2471.87
#Mann= 3 , 0 , 0
       0     .06       0   548.2    .045       0   563.2      .1       0
Bank Sta=548.2,563.2
XS Rating Curve= 0 ,0
Exp/Cntr=0.3,0.1

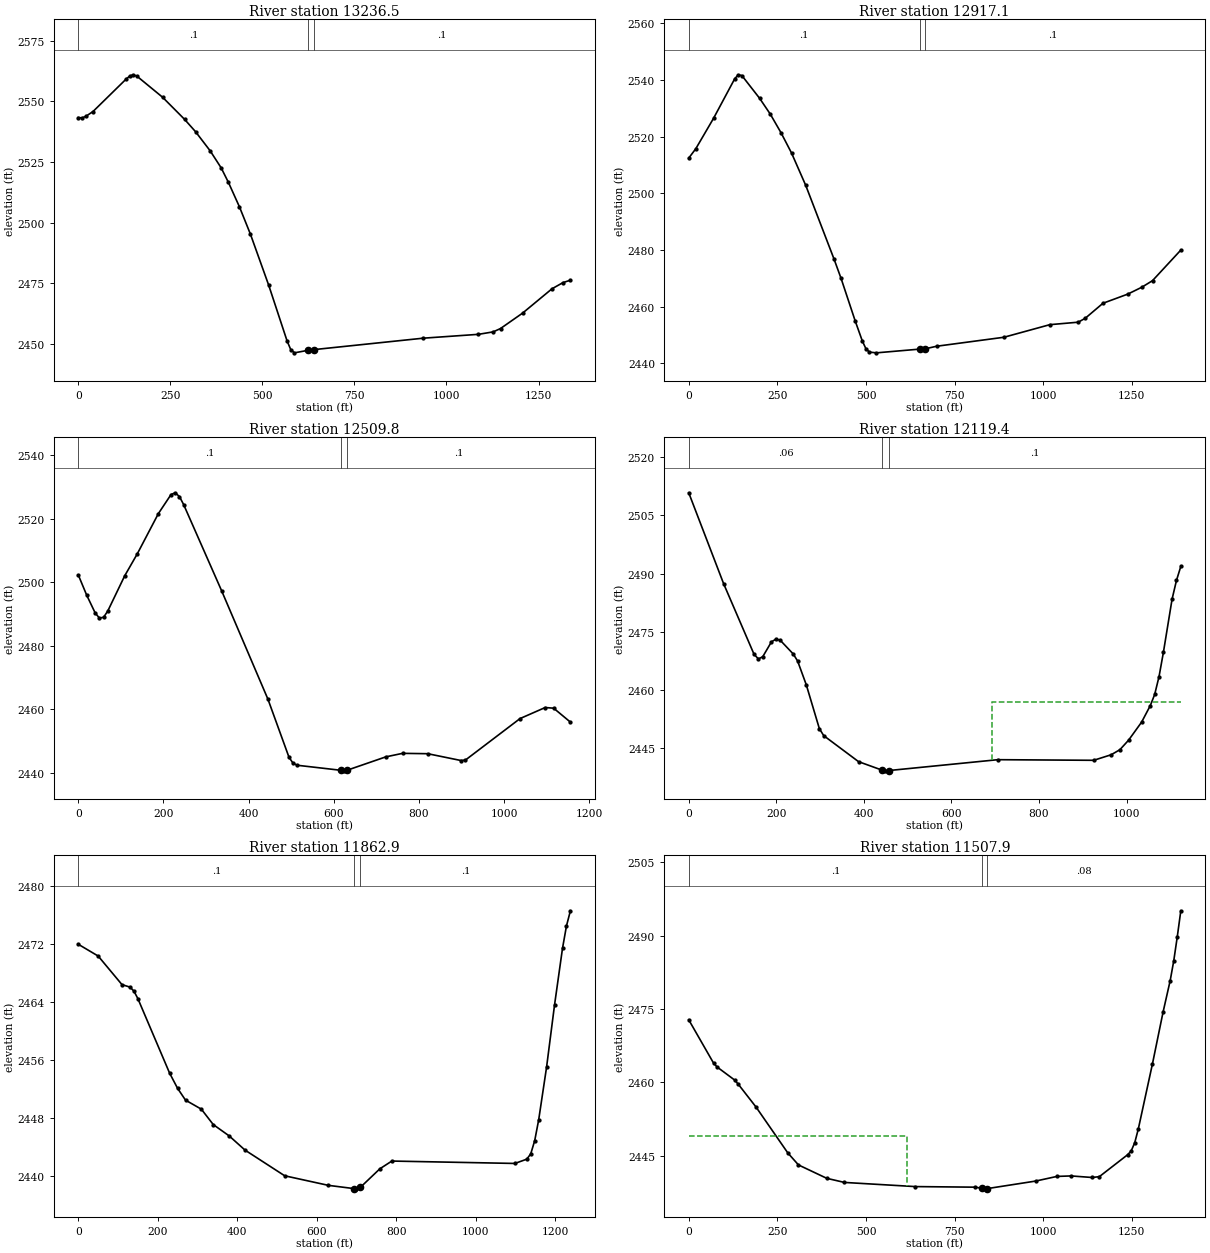
Type RM Length L Ch R = 1 ,13236.5 ,310.3,319.5,328.4
XS GIS Cut Line= 3
     2007634.582      319270.646     2007090.633       319430.59
     2006376.281      319716.967
#Sta/Elev= 30
       0 2543.35      10  2543.2    19.9 2543.81    39.8 2545.82   129.3 2559.15
   139.3 2560.44   149.2    2561   159.2 2560.42   228.8 2551.73   288.5 2542.61
   318.3 2537.52   358.1  2529.6   387.9 2522.59   407.8 2516.54   437.7 2506.45
   467.5 2495.18   517.2 2474.08     567 2451.12     577 2447.54     587 2446.21
   625.12447.286   640.12447.543   936.8 2452.26  1086.7 2453.85  1126.7 2454.86
  1146.7 2456.24  1206.7 2462.61  1286.6 2472.66  1316.6 2475.22  1336.6  2476.2
#Mann= 3 , 0 , 0
       0      .1       0   625.1    .045       0   640.1      .1       0
Bank Sta=625.1,640.1
XS Rating Curve= 0 ,0
Exp/Cntr=0.3,0.1

Type RM Length L Ch R = 1 ,12917.1 ,386,406.9,425.6
XS GIS Cut Line= 3
     2007502.248      319138.709     2007125.634       319188.76
     2006129.678      319344.677
#Sta/Elev= 30
       0 2512.44      20 2515.77      70 2526.49     130 2540.52     140 2541.86
     150 2541.57     200 2533.54     230 2527.98     260 2521.47   289.9 2514.26
   329.9 2502.85   409.9 2476.78   429.8 2469.94   469.8 2454.86   489.7 2447.86
   499.7 2445.17   509.7 2443.94   529.6 2443.69     6522445.012     6672445.112
   699.3 2446.02     889 2449.19  1018.7 2453.64  1098.6 2454.51  1118.5  2455.9
  1168.4 2461.19  1238.3 2464.42  1278.2 2466.87  1308.2 2469.18    1388 2479.97
#Mann= 3 , 0 , 0
       0      .1       0     652    .045       0     667      .1       0
Bank Sta=652,667
XS Rating Curve= 0 ,0
Exp/Cntr=0.3,0.1

Type RM Length L Ch R = 1 ,12509.8 ,381.8,390.4,401.2
XS GIS Cut Line= 3
     2007521.121      319056.188     2006937.901      318835.501
      2006430.08      318675.902
#Sta/Elev= 30
       0 2502.32    19.8 2495.94    39.6 2490.38    49.5 2488.78    59.4 2489.02
    69.3 2491.04   108.9 2502.08   138.6 2509.04   188.1 2521.71   217.8  2527.7
   227.7 2528.25   237.6 2527.04   247.4 2524.52   336.5  2497.4   445.4 2463.21
   494.9  2444.9   504.8 2442.97   514.7 2442.39   616.12440.822   623.6 2440.64
   631.12440.823   722.2 2445.04   761.6 2446.15   820.7 2446.04   899.6 2443.87
   909.4 2444.05  1037.6 2457.11  1096.7 2460.59  1116.5 2460.38  1155.9 2455.99
#Mann= 3 , 0 , 0
       0      .1       0   616.1    .045       0   631.1      .1       0
Bank Sta=616.1,631.1
XS Rating Curve= 0 ,0
Exp/Cntr=0.3,0.1

Type RM Length L Ch R = 1 ,12119.4 ,264.6,256.3,248.1
XS GIS Cut Line= 2
     2007580.656      318830.789     2006632.429      318227.806
#Sta/Elev= 30
       0 2510.84    79.6 2487.39   149.2 2469.13   159.1 2467.96     169 2468.52
   188.9 2472.36   198.9 2473.05   208.8 2472.79   238.7 2469.22   248.6 2467.42
   268.5 2461.25   298.3 2449.95   308.3 2448.14   387.8 2441.43   441.82439.227
   447.5 2439.06   456.82439.135     706 2441.94   924.8 2441.78   964.6 2443.21
   984.5 2444.51  1004.4 2446.97  1034.2 2451.64  1054.1 2455.92    1064 2458.77
    1074 2463.41  1083.9 2469.62  1103.8 2483.41  1113.8 2488.22  1123.7 2491.83
#Mann= 3 , 0 , 0
       0     .06       0   441.8    .045       0   456.8      .1       0
#XS Ineff= 2 , 0
                          693.09         2456.89
Permanent Ineff=
       F       F
Bank Sta=441.8,456.8
XS Rating Curve= 0 ,0
Exp/Cntr=0.3,0.1

Type RM Length L Ch R = 1 ,11862.9 ,368.4,354.9,341.3
XS GIS Cut Line= 2
     2007892.925       318600.74     2006738.255      318154.402
#Sta/Elev= 30
       0 2471.93    49.9 2470.31   109.8 2466.37   129.8 2466.03   139.8 2465.48
   149.8 2464.44   229.6 2454.17   249.6 2452.08   269.6 2450.45   309.5  2449.2
   339.4 2447.08   379.4 2445.52   419.3 2443.56   519.1 2440.02     629  2438.7
   694.32438.247   698.8 2438.22   709.32438.417   758.7 2440.99   788.7 2442.05
  1098.2 2441.72  1128.1 2442.31  1138.1 2443.04  1148.1 2444.87  1158.1 2447.74
    1178 2455.02    1198 2463.58    1218 2471.37    1228 2474.47  1237.9 2476.55
#Mann= 3 , 0 , 0
       0      .1       0   694.3    .045       0   709.3      .1       0
Bank Sta=694.3,709.3
XS Rating Curve= 0 ,0
Exp/Cntr=0.3,0.1

Type RM Length L Ch R = 1 ,11507.9 ,191.4,198.1,203
XS GIS Cut Line= 2
     2008089.771      318038.479     2006702.433      317987.567
#Sta/Elev= 30
       0 2472.81    69.9 2463.97    79.9 2463.16   129.8 2460.47   139.8 2459.63
   189.8 2454.97   279.6 2445.57   309.6 2443.12   389.5 2440.38   439.4 2439.54
   639.2 2438.69     809 2438.57   827.62438.323     839 2438.23   842.62438.284
   978.8 2439.82  1038.7 2440.77  1078.7 2440.87  1138.6 2440.55  1158.6 2440.73
  1238.5 2445.22  1248.4    2446  1258.4 2447.69  1268.4 2450.48  1308.4 2463.83
  1338.3 2474.41  1358.3 2480.82  1368.3 2484.84  1378.3 2489.78  1388.3 2495.11
#Mann= 3 , 0 , 0
       0      .1       0   827.6    .045       0   842.6     .08       0
#XS Ineff= 2 , 0
           617.2 2449.07
Permanent Ineff=
       F       F
Bank Sta=827.6,842.6
XS Rating Curve= 0 ,0
Exp/Cntr=0.3,0.1