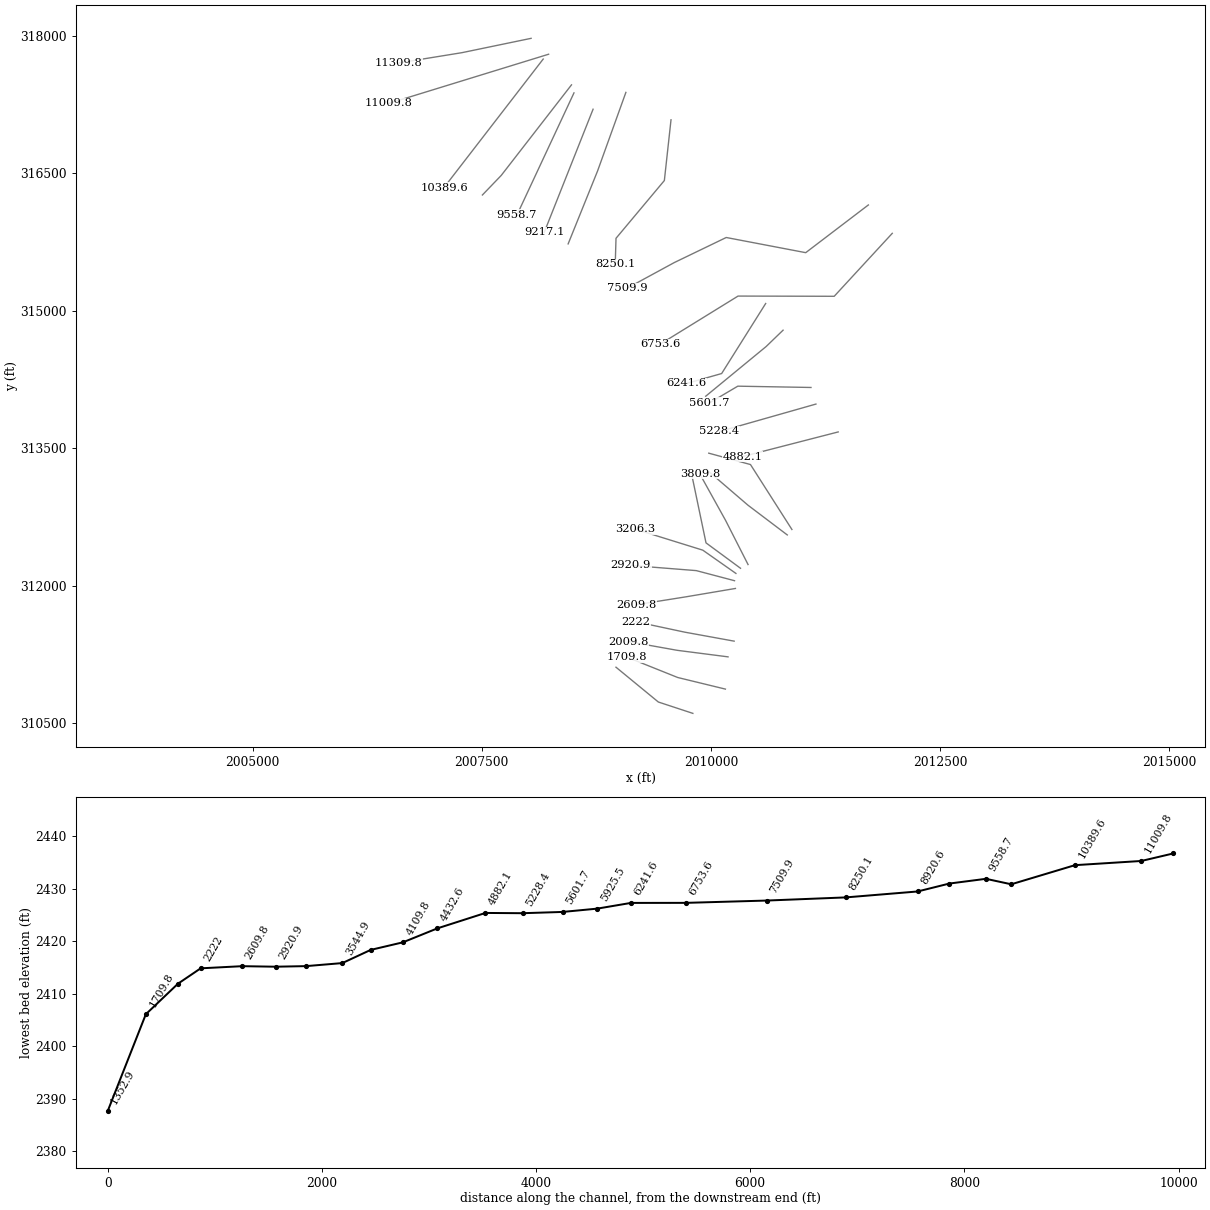
HEC-RAS study MeadowCrk.prj: MeadowCrk

--- MeadowCrk.g01 (geometry) --- (continued)

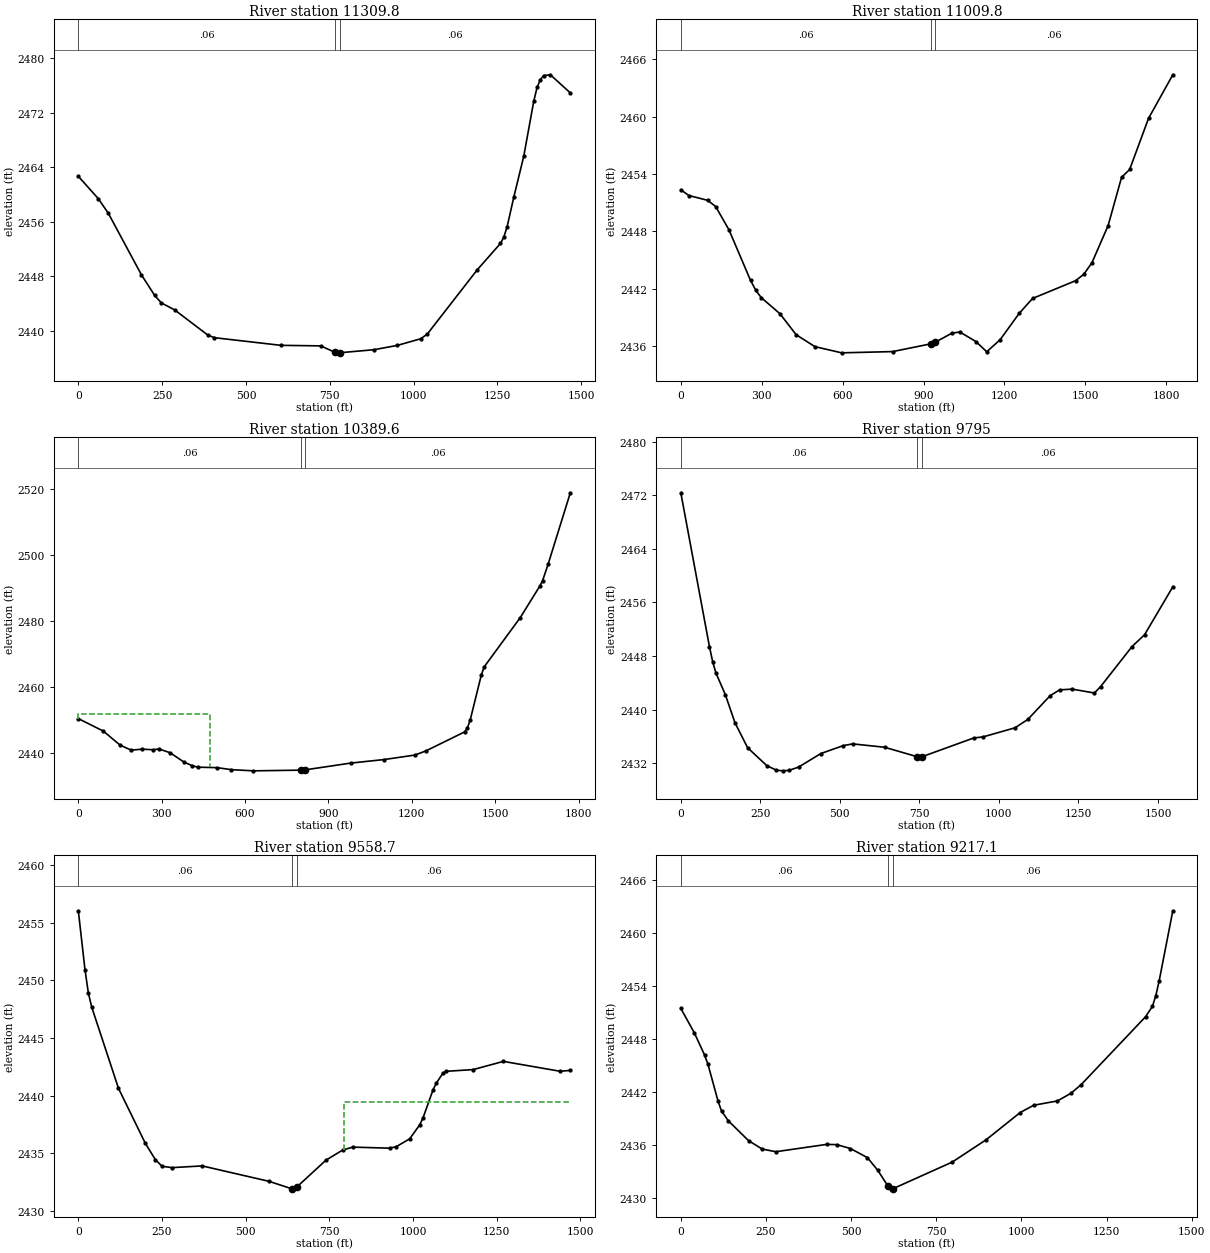
Type RM Length L Ch R = 1 ,11309.8 ,295.9,299.8,305.6
XS GIS Cut Line= 3
     2008038.859      317971.657      2007282.37       317814.93
     2006596.526      317703.791
#Sta/Elev= 30
       0 2462.65    59.4 2459.38    89.1 2457.26   188.2  2448.2   227.8 2445.17
   247.6 2444.08   287.2 2443.06   386.3 2439.36   406.1 2438.98   604.2 2437.86
     723 2437.78   765.12436.843   772.6 2436.76   780.12436.775   881.7 2437.22
   951.2 2437.85  1020.7 2438.82  1040.5  2439.5  1189.4 2448.92  1258.9  2452.8
  1268.8 2453.72  1278.8 2455.25  1298.6 2459.57  1328.4 2465.59  1358.2 2473.65
  1368.1 2475.68    1378 2476.83  1387.9 2477.43  1407.8 2477.54  1467.3 2474.88
#Mann= 3 , 0 , 0
       0     .06       0   765.1    .045       0   780.1     .06       0
Bank Sta=765.1,780.1
XS Rating Curve= 0 ,0
Exp/Cntr=0.3,0.1

Type RM Length L Ch R = 1 ,11009.8 ,594.6,620.2,645.5
XS GIS Cut Line= 3
     2008229.777       317798.24     2007336.769       317523.65
      2006486.07      317261.968
#Sta/Elev= 30
       0 2452.35    29.8 2451.75    99.4 2451.25   129.2  2450.6   178.9 2448.15
   258.4 2442.89   278.3 2441.84   298.2 2441.09   367.8  2439.4   427.4 2437.22
     497 2435.97   596.3 2435.32   785.2 2435.45   926.82436.258   941.82436.407
  1004.3 2437.36  1034.3  2437.5  1094.3  2436.5  1134.3 2435.43  1184.3  2436.7
  1254.3 2439.43  1304.3    2441  1464.3 2442.86  1494.3 2443.53  1524.3 2444.72
  1584.3  2448.6  1634.3 2453.65  1664.3 2454.47  1734.3 2459.81  1824.3 2464.36
#Mann= 3 , 0 , 0
       0     .06       0   926.8    .045       0   941.8     .06       0
Bank Sta=926.8,941.8
XS Rating Curve= 0 ,0
Exp/Cntr=0.3,0.1

Type RM Length L Ch R = 1 ,10389.6 ,568.4,594.4,591.1
XS GIS Cut Line= 2
     2008170.911      317745.737     2007088.626      316344.502
#Sta/Elev= 30
       0 2450.35      90 2446.56     150 2442.33   190.1 2440.79   230.1 2441.09
   270.1  2440.9   290.1 2441.15   330.1 2440.01   380.1 2437.18   410.1 2436.07
   430.1 2435.63   500.2 2435.48   550.2 2434.88   630.2 2434.52   800.92434.732
   815.92434.811   980.3 2436.87  1100.3 2437.94  1210.4 2439.29  1250.4 2440.54
  1390.4 2446.33  1400.4  2447.6  1410.4 2449.99  1450.4 2463.63  1460.4 2466.01
  1590.5 2480.96  1660.5 2490.46  1670.5  2492.1  1690.5  2497.1  1770.5 2518.76
#Mann= 3 , 0 , 0
       0     .06       0   800.9    .045       0   815.9     .06       0
#XS Ineff= 2 , 0
          473.12 2451.81
Permanent Ineff=
       F       F
Bank Sta=800.9,815.9
XS Rating Curve= 0 ,0
Exp/Cntr=0.3,0.1

Type RM Length L Ch R = 1 ,9795    ,229,236.5,245.1
XS GIS Cut Line= 3
     2008479.562      317464.133     2007712.708      316476.132
     2007507.471       316262.94
#Sta/Elev= 30
       0 2472.36      90 2449.41     100 2447.19   110.1 2445.51   140.1 2442.23
   170.1 2438.07   210.1 2434.32   270.2 2431.66   300.2 2430.98   320.2 2430.88
   340.2 2430.95   370.2 2431.44   440.2 2433.46   510.3 2434.64   540.3  2434.9
   640.4  2434.4   743.52432.981   758.52432.989   920.5 2435.78   950.5 2435.95
  1050.6  2437.3  1090.6 2438.54  1160.6 2442.07  1190.6 2442.96  1230.7 2443.07
    1300 2442.49  1319.7 2443.45  1418.4 2449.42  1457.8 2451.18  1546.6 2458.33
#Mann= 3 , 0 , 0
       0     .06       0   743.5    .045       0   758.5     .06       0
Bank Sta=743.5,758.5
XS Rating Curve= 0 ,0
Exp/Cntr=0.3,0.1

Type RM Length L Ch R = 1 ,9558.7  ,335.7,341.3,345.5
XS GIS Cut Line= 2
     2008506.609      317376.629     2007884.534      316044.975
#Sta/Elev= 30
       0 2456.05      20 2450.91      30 2448.91      40 2447.69     120 2440.64
     200 2435.88     230 2434.46     250 2433.88     280 2433.76     370 2433.91
   569.9 2432.57   636.92431.932   639.9 2431.92   651.92432.058   739.9 2434.41
   789.9 2435.29   819.9 2435.54   929.9 2435.45   949.9 2435.58   989.9 2436.26
  1019.8 2437.47  1029.8 2438.08  1059.8 2440.52  1069.8 2441.11  1089.8 2441.98
  1099.8 2442.12  1179.8 2442.27  1269.8 2442.98  1439.8 2442.12  1469.8  2442.2
#Mann= 3 , 0 , 0
       0     .06       0   636.9    .045       0   651.9     .06       0
#XS Ineff= 2 , 0
                          793.86         2439.49
Permanent Ineff=
       F       F
Bank Sta=636.9,651.9
XS Rating Curve= 0 ,0
Exp/Cntr=0.3,0.1

Type RM Length L Ch R = 1 ,9217.1  ,295.2,296.5,296.4
XS GIS Cut Line= 2
     2008715.028      317198.439     2008182.048      315855.648
#Sta/Elev= 30
       0 2451.44    39.8 2448.67    69.7 2446.17    79.7 2445.12   109.6 2440.91
   119.6 2439.82   139.5 2438.72   199.3 2436.46   239.1 2435.52     279 2435.22
   428.4 2436.05   458.3 2436.02   498.2 2435.58     548 2434.55   577.9 2433.14
   608.32431.333   617.7 2431.02   623.32431.042   797.1 2434.05   896.7 2436.58
   996.3 2439.65  1036.2 2440.48  1105.9 2440.97  1145.8 2441.84  1175.7 2442.82
    1365 2450.51  1384.9 2451.68  1394.9  2452.9  1404.8 2454.59  1444.7 2462.49
#Mann= 3 , 0 , 0
       0     .06       0   608.3    .045       0   623.3     .06       0
Bank Sta=608.3,623.3
XS Rating Curve= 0 ,0
Exp/Cntr=0.3,0.1

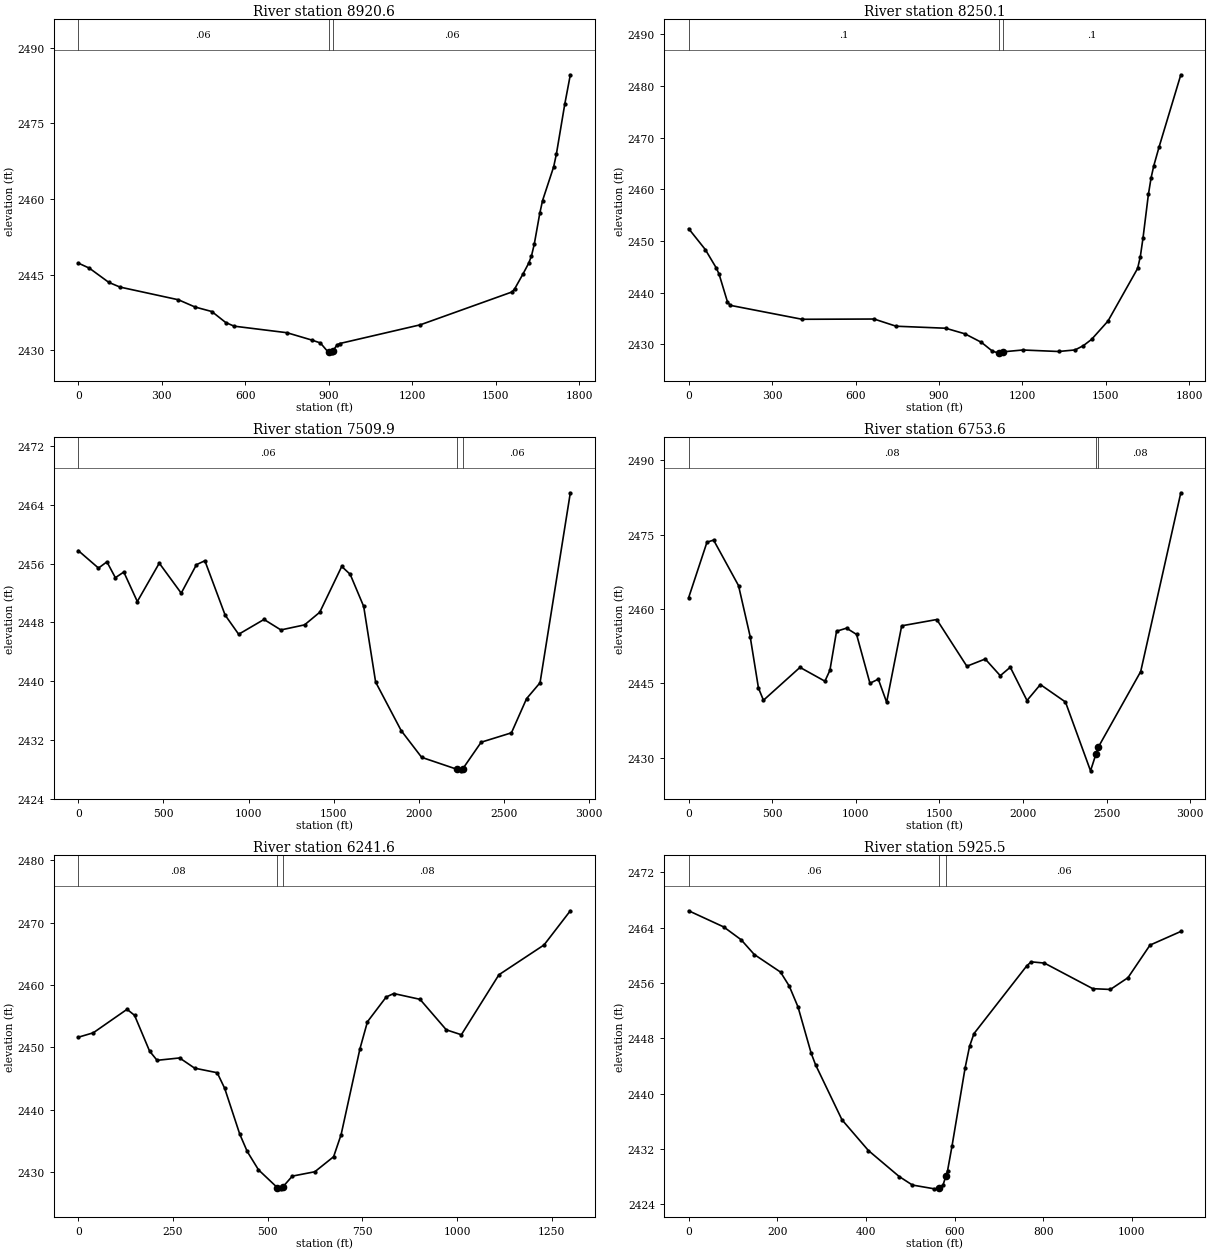
Type RM Length L Ch R = 1 ,8920.6  ,683.7,670.5,657.6
XS GIS Cut Line= 3
     2009072.999      317381.932     2008764.348      316525.453
     2008442.969       315729.43
#Sta/Elev= 30
       0 2447.31      40  2446.3     110 2443.48   150.1 2442.55   360.2 2440.03
   420.2 2438.59   480.2  2437.7   530.2 2435.52   560.2  2434.8   750.3  2433.5
   840.4 2432.03   870.4 2431.47   899.7 2429.58   910.4 2429.51   914.72429.867
   930.4 2431.07   940.3 2431.36  1229.8 2435.07  1559.2 2441.58  1569.2 2442.24
  1599.2  2445.2  1619.1 2447.28  1629.1 2448.71  1639.1 2451.03    1659 2457.17
    1669  2459.7    1709 2466.41  1718.9 2468.99  1748.9 2478.84  1768.8 2484.64
#Mann= 3 , 0 , 0
       0     .06       0   899.7    .045       0   914.7     .06       0
Bank Sta=899.7,914.7
XS Rating Curve= 0 ,0
Exp/Cntr=0.3,0.1

Type RM Length L Ch R = 1 ,8250.1  ,758.1,739,721.2
XS GIS Cut Line= 4
     2009565.515      317083.147     2009492.845      316420.461
     2008965.267      315790.305     2008956.872       315509.07
#Sta/Elev= 30
       0 2452.39    59.7 2448.36    99.5 2444.77   109.4 2443.58   139.3 2438.26
   149.2 2437.57     408 2434.87   666.7 2434.92   745.9 2433.53   924.1 2433.14
   993.4 2432.06  1052.8 2430.41  1092.4  2428.7  1112.2 2428.38  1116.72428.407
  1128.72428.567  1201.4 2428.93  1330.1 2428.64  1389.5 2428.94  1419.2 2429.76
  1448.9 2430.98  1507.9 2434.52  1614.6 2444.71  1624.3 2446.99    1634 2450.61
  1653.4 2459.05  1663.2 2462.28  1672.8 2464.58  1692.2 2468.28  1769.9 2482.16
#Mann= 3 , 0 , 0
       0      .1       0  1116.7    .045       0  1128.7      .1       0
Bank Sta=1116.7,1128.7
XS Rating Curve= 0 ,0
Exp/Cntr=0.3,0.1

Type RM Length L Ch R = 1 ,7509.9  ,751.4,755.8,759.4
BEGIN DESCRIPTION:
Rating curved added at 8322.3 to correspond with effective WSEL at XS-M.  Channel invert was dropped to correspond to effective profile to allow rating curve to work
END DESCRIPTION:
XS GIS Cut Line= 5
     2011719.028      316154.187     2011035.431      315633.689
      2010168.14      315799.159     2009600.406      315525.278
     2009088.304      315247.117
#Sta/Elev= 30
       0  2457.8     119 2455.41   168.5 2456.26   218.1  2454.1   267.7 2454.87
     347 2450.85   475.9 2456.08   604.8 2451.99     694 2455.87   743.6 2456.41
   862.6    2449     942 2446.39  1090.8 2448.41    1190 2446.98  1328.9 2447.67
  1418.1 2449.39  1547.1 2455.63  1596.7 2454.56  1676.1 2450.18  1746.1 2439.88
  1896.2 2433.26  2016.3 2429.62  2226.4 2427.97  2246.4 2427.78  2256.4 2428.01
  2365.7 2431.68  2543.5 2432.96  2632.4 2437.62  2711.4 2439.78  2889.2 2465.67
#Mann= 3 , 0 , 0
       0     .06       0  2226.4    .045       0  2256.4     .06       0
Bank Sta=2226.4,2256.4
XS Rating Curve= 0 ,0
Exp/Cntr=0.3,0.1

Type RM Length L Ch R = 1 ,6753.6  ,493,511.7,530.4
XS GIS Cut Line= 4
     2011979.904      315844.688      2011346.34      315157.874
     2010296.996      315160.211     2009445.937      314635.117
#Sta/Elev= 30
       0 2462.33   109.3  2473.5     149 2473.93   298.1 2464.74   367.7 2454.46
   417.3 2444.06   447.2 2441.59   665.8 2448.23   814.8 2445.44   844.6 2447.63
   884.4 2455.52   944.3 2456.15  1004.2 2454.88  1084.2 2445.02  1134.2 2445.85
  1184.1 2441.19  1274.1 2456.62  1483.9 2457.89  1663.8 2448.46  1773.8 2449.92
  1863.7 2446.55  1923.7 2448.26  2023.6 2441.54  2103.6 2444.76  2253.7 2441.24
  2403.7 2427.34  2435.72430.688  2450.72432.157  2703.7 2447.38  2943.7 2483.48
#Mann= 3 , 0 , 0
       0     .08       0  2435.7    .045       0  2450.7     .08       0
Bank Sta=2435.7,2450.7
XS Rating Curve= 0 ,0
Exp/Cntr=0.3,0.1

Type RM Length L Ch R = 1 ,6241.6  ,328.6,315.2,287.1
XS GIS Cut Line= 3
     2010598.368      315079.046     2010118.099      314315.222
     2009736.263      314207.035
#Sta/Elev= 30
       0 2451.64    39.7 2452.35   128.9 2456.12   148.7 2455.16   188.4 2449.42
   208.2 2447.94   267.7 2448.32   307.4 2446.68   366.9 2445.95   386.7 2443.44
   426.4 2436.11   446.2 2433.32   475.9 2430.38   525.92427.512   535.4 2427.33
   540.92427.691   565.2 2429.37   624.6 2430.07   674.2 2432.48     694 2436.02
   743.6 2449.76   763.5 2454.12     813 2458.09   832.9 2458.65   902.3 2457.72
   971.7 2452.83  1011.4 2452.04  1110.6 2461.66  1229.7 2466.44  1299.1 2471.92
#Mann= 3 , 0 , 0
       0     .08       0   525.9    .045       0   540.9     .08       0
Bank Sta=525.9,540.9
XS Rating Curve= 0 ,0
Exp/Cntr=0.3,0.1

Type RM Length L Ch R = 1 ,5925.5  ,352.2,323.8,295.3
XS GIS Cut Line= 3
     2010788.434      314788.275     2010603.879      314610.084
     2009944.187      314067.837
#Sta/Elev= 30
       0 2466.43    78.9  2464.1   118.4 2462.24     148 2460.11   207.2 2457.57
   226.9 2455.55   246.7 2452.53   276.4 2445.84   286.3 2444.17   345.9 2436.22
   405.5 2431.78     475 2428.02   504.8 2426.79   554.4 2426.24   565.62426.315
   574.3 2426.86   580.62428.139   584.2 2428.87   594.2 2432.42   623.9 2443.77
   633.9 2446.86   643.8 2448.68     763 2458.48   772.9 2459.05   802.7 2458.87
   911.9 2455.17   951.6 2455.06   991.3 2456.76    1041 2461.47  1110.5 2463.44
#Mann= 3 , 0 , 0
       0     .06       0   565.6    .045       0   580.6     .06       0
Bank Sta=565.6,580.6
XS Rating Curve= 0 ,0
Exp/Cntr=0.3,0.1

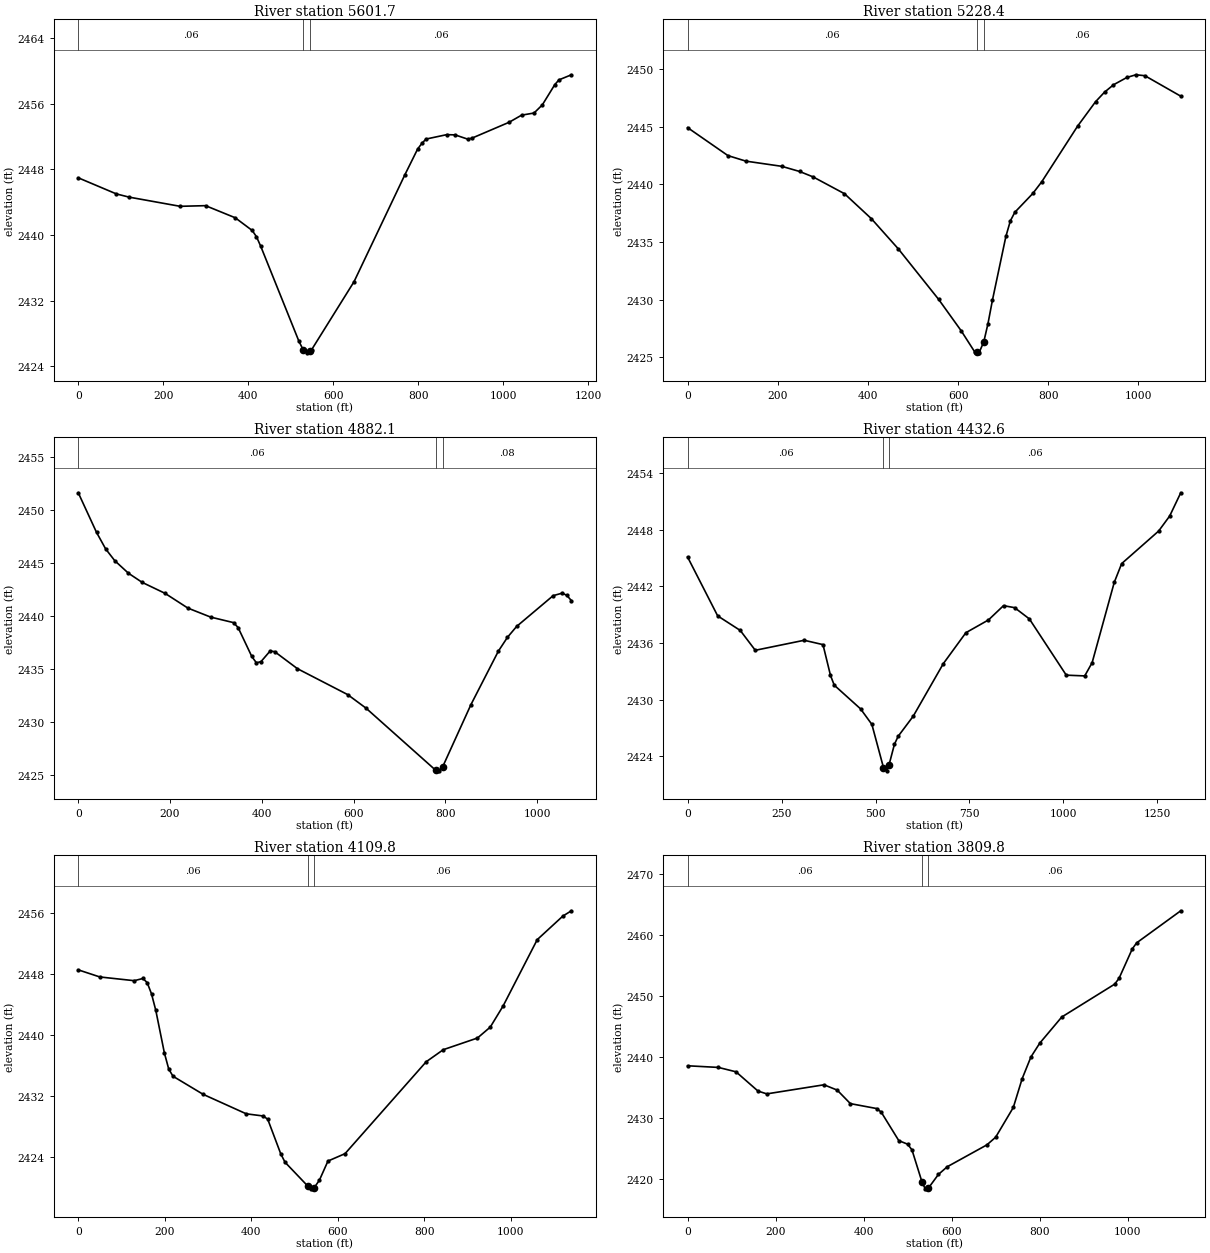
Type RM Length L Ch R = 1 ,5601.7  ,359.7,373.3,385.9
XS GIS Cut Line= 3
     2011092.933      314163.194     2010294.168      314177.337
     2009982.605      313993.362
#Sta/Elev= 30
       0 2446.98    89.9 2445.01   119.8 2444.62   239.7  2443.5   299.6 2443.58
   369.5  2442.1   409.4 2440.55   419.4 2439.79   429.4 2438.63   519.3 2427.03
   529.62425.959   539.2 2425.61   544.62425.815   549.2 2425.99   649.1  2434.3
   768.9 2447.37   798.9 2450.51   808.7 2451.18   818.4 2451.71   867.3 2452.25
   886.9 2452.22   916.2 2451.71     926 2451.81    1014 2453.76  1043.4 2454.63
  1072.7 2454.89  1092.3 2455.89  1121.6 2458.36  1131.4 2458.94  1160.7 2459.56
#Mann= 3 , 0 , 0
       0     .06       0   529.6    .045       0   544.6     .06       0
Bank Sta=529.6,544.6
XS Rating Curve= 0 ,0
Exp/Cntr=0.3,0.1

Type RM Length L Ch R = 1 ,5228.4  ,349,346.2,344.4
XS GIS Cut Line= 2
     2011146.935      313982.176     2010094.764      313683.071
#Sta/Elev= 30
       0 2444.93    89.5  2442.5   129.3 2442.02   208.8 2441.57   248.6 2441.12
   278.4 2440.65     348 2439.19   407.7 2437.02   467.4  2434.4   556.9 2430.01
   606.6  2427.3   636.4 2425.48     6422425.418   646.4 2425.37     6572426.329
   666.3 2427.91   676.2 2429.95     706 2435.48     716 2436.84   725.9 2437.58
   765.7 2439.21   785.6 2440.23   865.1 2445.06   904.9 2447.18   924.8 2448.01
   944.7 2448.65   974.5 2449.29   994.4 2449.52  1014.3 2449.44  1093.9 2447.66
#Mann= 3 , 0 , 0
       0     .06       0     642    .045       0     657     .06       0
Bank Sta=642,657
XS Rating Curve= 0 ,0
Exp/Cntr=0.3,0.1

Type RM Length L Ch R = 1 ,4882.1  ,499.9,449.4,399
XS GIS Cut Line= 2
     2011390.019       313678.24     2010349.477      313410.235
#Sta/Elev= 30
       0 2451.61    39.8 2447.88    59.7 2446.32    79.6 2445.21   109.4 2444.03
   139.3 2443.17     189 2442.14   238.8 2440.75   288.5  2439.9   338.3 2439.38
   348.2 2438.92   378.1 2436.19     388  2435.6     398  2435.7   417.9  2436.7
   427.8 2436.65   477.6 2435.04     587  2432.6   626.8 2431.33   779.12425.461
     786 2425.42   794.12425.813   855.6 2431.66   915.3 2436.69   935.2    2438
   955.1 2439.02  1034.7 2441.92  1054.6 2442.16  1064.6 2441.94  1074.5 2441.45
#Mann= 3 , 0 , 0
       0     .06       0   779.1    .045       0   794.1     .08       0
Bank Sta=779.1,794.1
XS Rating Curve= 0 ,0
Exp/Cntr=0.3,0.1

Type RM Length L Ch R = 1 ,4432.6  ,308.9,322.1,326.8
XS GIS Cut Line= 3
     2010884.765      312613.973     2010432.583      313322.448
     2009977.562      313446.545
#Sta/Elev= 30
       0 2445.09      80 2438.87   140.1 2437.33   180.1 2435.23   310.2 2436.29
   360.2 2435.83   380.2 2432.57   390.2 2431.54   460.3 2429.03   490.3 2427.39
   521.1 2422.83   530.3 2422.48   536.12423.135   550.3 2425.29   560.3 2426.14
   600.3 2428.26   680.4 2433.82   740.4 2437.09   800.5 2438.44   840.5 2439.95
     870 2439.74   909.3 2438.55  1007.5  2432.6  1056.6 2432.52  1076.3 2433.92
  1135.2 2442.42  1154.9  2444.4  1253.2 2447.84  1282.6 2449.43  1312.1 2451.89
#Mann= 3 , 0 , 0
       0     .06       0   521.1    .045       0   536.1     .06       0
Bank Sta=521.1,536.1
XS Rating Curve= 0 ,0
Exp/Cntr=0.3,0.1

Type RM Length L Ch R = 1 ,4109.8  ,317.7,300.4,292.8
XS GIS Cut Line= 3
     2010834.089      312554.684     2010405.267      312879.013
     2009948.199      313271.363
#Sta/Elev= 30
       0 2448.51    49.8 2447.58   129.4 2447.09   149.4 2447.38   159.3 2446.84
   169.3 2445.37   179.2 2443.21   199.1 2437.62   209.1 2435.52     219 2434.57
   288.7  2432.2   388.3 2429.65   428.1 2429.36   438.1 2428.92     468 2424.42
   477.9 2423.31   530.22420.203   537.7 2419.82   545.22419.958   557.4 2420.95
   577.2 2423.46   616.7 2424.43   804.3 2436.47   843.8 2438.05   922.8 2439.58
   952.4 2441.01     982 2443.77    1061 2452.47  1120.3 2455.56    1140 2456.25
#Mann= 3 , 0 , 0
       0     .06       0   530.2    .045       0   545.2     .06       0
Bank Sta=530.2,545.2
XS Rating Curve= 0 ,0
Exp/Cntr=0.3,0.1

Type RM Length L Ch R = 1 ,3809.8  ,275.3,264.7,252.8
XS GIS Cut Line= 3
     2010406.163       312231.71     2010161.215      312712.775
     2009879.371      313220.534
#Sta/Elev= 30
       0 2438.57      70  2438.3     110 2437.58     160 2434.42     180 2433.96
   309.9 2435.45   339.9 2434.58   369.9 2432.36   429.9 2431.55   439.9 2430.97
   479.9 2426.29   499.8 2425.71   509.8 2424.78   532.3 2419.58   539.8 2418.38
   547.32418.515   569.9 2420.74   589.9    2422     680 2425.59     700 2426.85
   740.1 2431.73   760.1 2436.43   780.1 2440.01   800.2 2442.28   850.2 2446.57
   970.4 2451.96   980.4 2452.92  1010.4 2457.74  1020.4 2458.74  1120.6    2464
#Mann= 3 , 0 , 0
       0     .06       0   532.3    .045       0   547.3     .06       0
Bank Sta=532.3,547.3
XS Rating Curve= 0 ,0
Exp/Cntr=0.3,0.1

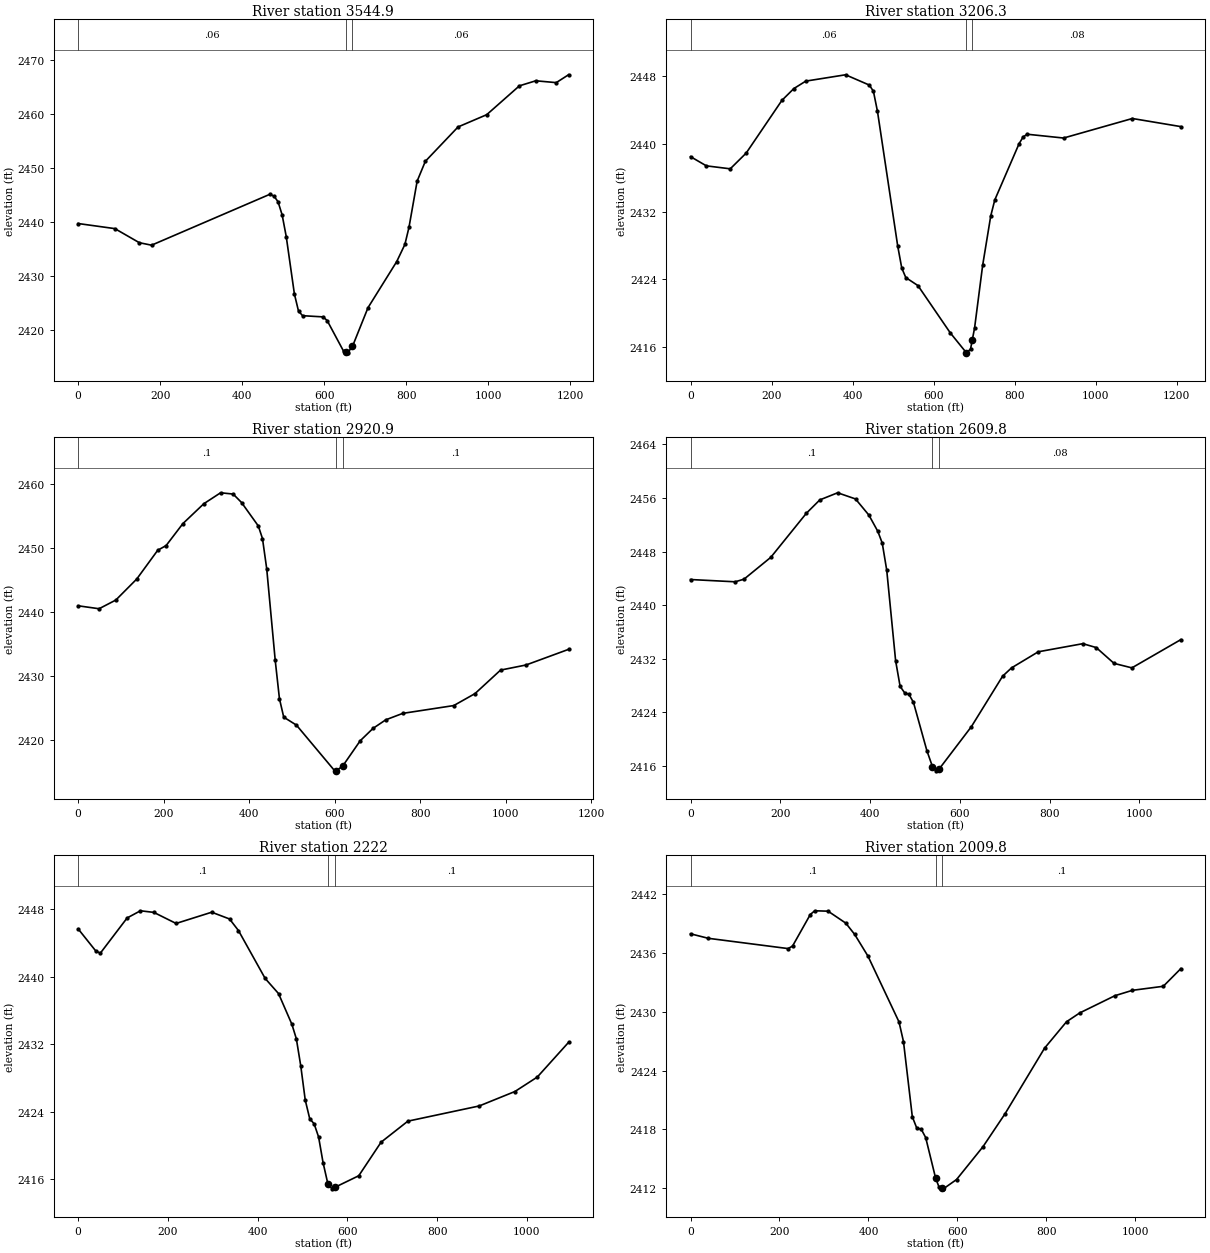
Type RM Length L Ch R = 1 ,3544.9  ,296,338.6,381.2
XS GIS Cut Line= 3
     2010323.839      312191.145     2009947.333      312468.089
     2009798.299      313180.696
#Sta/Elev= 30
       0 2439.75    89.5 2438.81   149.2 2436.21     179 2435.75   467.4 2445.15
   477.4 2444.81   487.3 2443.78   497.3 2441.35   507.3 2437.35   527.2 2426.74
   537.2 2423.58   547.2 2422.73     597 2422.51     607 2421.84   646.9  2416.2
   653.82415.972   656.9 2415.87   668.82417.066   706.7 2424.22   776.6 2432.72
   796.5 2435.88   806.5 2439.04   826.4 2447.58   846.4 2451.24   926.2 2457.59
     996 2459.85  1075.7 2465.18  1115.6 2466.11  1165.5 2465.77  1195.4 2467.22
#Mann= 3 , 0 , 0
       0     .06       0   653.8    .045       0   668.8     .06       0
Bank Sta=653.8,668.8
XS Rating Curve= 0 ,0
Exp/Cntr=0.3,0.1

Type RM Length L Ch R = 1 ,3206.3  ,276.1,285.2,294.2
XS GIS Cut Line= 3
     2010273.676      312134.818     2009912.332       312388.54
     2009178.039      312616.665
#Sta/Elev= 30
       0 2438.49    39.2  2437.4    98.1 2437.05   137.4 2438.91   225.7 2445.15
   255.1 2446.54   284.5 2447.42   382.7 2448.17   441.5 2446.95   451.5 2446.21
   461.5 2443.84   511.4 2427.93   521.4 2425.32   531.4 2424.19   561.4 2423.24
   641.2 2417.65   680.72415.313   681.2 2415.29   691.2 2415.74   695.72416.865
   701.2 2418.24   721.1 2425.64   741.1 2431.49   751.1 2433.38     811 2440.02
     821 2440.82     831 2441.14   920.8 2440.69  1090.6    2443  1210.4 2442.04
#Mann= 3 , 0 , 0
       0     .06       0   680.7    .045       0   695.7     .08       0
Bank Sta=680.7,695.7
XS Rating Curve= 0 ,0
Exp/Cntr=0.3,0.1

Type RM Length L Ch R = 1 ,2920.9  ,301.3,311.1,320.5
XS GIS Cut Line= 3
      2010258.43      312055.439     2009841.533      312165.405
     2009127.891      312222.008
#Sta/Elev= 30
       0 2440.97      49 2440.51    88.2 2441.87   137.2 2445.16   186.2 2449.65
   205.8 2450.38     245 2453.81     294 2456.92   333.2 2458.63   362.6 2458.43
   382.2 2457.11   421.4 2453.45   431.2 2451.48   441.1 2446.76     461 2432.44
   470.9 2426.44   480.9 2423.57   510.7 2422.32   600.2 2415.18   603.52415.203
   618.52415.897   659.8 2419.88   689.7 2421.81   719.5 2423.15   759.3 2424.16
   878.6 2425.38   928.3 2427.25     988 2430.92  1047.6 2431.72    1147 2434.16
#Mann= 3 , 0 , 0
       0      .1       0   603.5    .045       0   618.5      .1       0
Bank Sta=603.5,618.5
XS Rating Curve= 0 ,0
Exp/Cntr=0.3,0.1

Type RM Length L Ch R = 1 ,2609.8  ,402.4,388,373.3
XS GIS Cut Line= 3
     2010268.357      311970.786     2009729.431      311879.688
     2009189.981      311793.884
#Sta/Elev= 30
       0 2443.82    99.4 2443.48   119.2 2443.87   178.9 2447.13   258.4 2453.72
   288.2  2455.7   327.9 2456.76   367.7 2455.84   397.5 2453.43   417.4 2451.01
   427.3 2449.25   437.3  2445.2   457.1  2431.7   467.1 2427.88     477 2426.94
     487 2426.67   496.9 2425.48   526.7  2418.3   539.12415.925   546.6 2415.28
   554.12415.553     626 2421.88   695.5  2429.4   715.4 2430.64     775 2433.04
   874.3 2434.25   904.1 2433.67   943.8 2431.31   983.6 2430.64  1092.8 2434.86
#Mann= 3 , 0 , 0
       0      .1       0   539.1    .045       0   554.1     .08       0
Bank Sta=539.1,554.1
XS Rating Curve= 0 ,0
Exp/Cntr=0.3,0.1

Type RM Length L Ch R = 1 ,2222    ,209.3,212,213.3
XS GIS Cut Line= 3
     2010254.592       311396.05     2009717.559      311493.691
     2009182.629      311607.608
#Sta/Elev= 30
       0 2445.64    39.7    2443    49.6 2442.77   109.2 2446.93   138.9 2447.78
   168.7 2447.59   218.3 2446.28   297.7 2447.61   337.4 2446.81   357.3 2445.44
   416.8 2439.77   446.6 2437.98   476.4 2434.34   486.3 2432.63   496.2  2429.4
   506.1 2425.38   516.1 2423.17     526 2422.56   535.9    2421   545.8 2417.98
   556.52415.474   565.7 2414.87   571.52415.032   625.4 2416.42   675.1 2420.39
   734.8 2422.88   893.9 2424.68   973.4 2426.39  1023.2  2428.1  1092.8  2432.2
#Mann= 3 , 0 , 0
       0      .1       0   556.5    .045       0   571.5      .1       0
Bank Sta=556.5,571.5
XS Rating Curve= 0 ,0
Exp/Cntr=0.3,0.1

Type RM Length L Ch R = 1 ,2009.8  ,304.5,299.8,291.6
XS GIS Cut Line= 3
     2010187.893      311224.727     2009633.972      311295.901
     2009098.668      311391.646
#Sta/Elev= 30
       0 2437.98    39.9 2437.52   219.4 2436.47   229.4 2436.73   269.3 2439.95
   279.2 2440.33   309.2 2440.29     349 2439.07     369 2437.92   398.9  2435.7
   468.7 2428.98   478.7 2426.98   498.6  2419.3   508.6 2418.14   518.6 2418.03
   528.6 2417.18     5512413.025   558.5 2412.14     5662411.989   568.4 2411.94
     598 2412.89   657.4 2416.24   706.8 2419.59   795.8  2426.3   845.2    2429
   874.9  2429.9     954 2431.66   993.5 2432.21  1062.7 2432.62  1102.3 2434.43
#Mann= 3 , 0 , 0
       0      .1       0     551    .045       0     566      .1       0
Bank Sta=551,566
XS Rating Curve= 0 ,0
Exp/Cntr=0.3,0.1

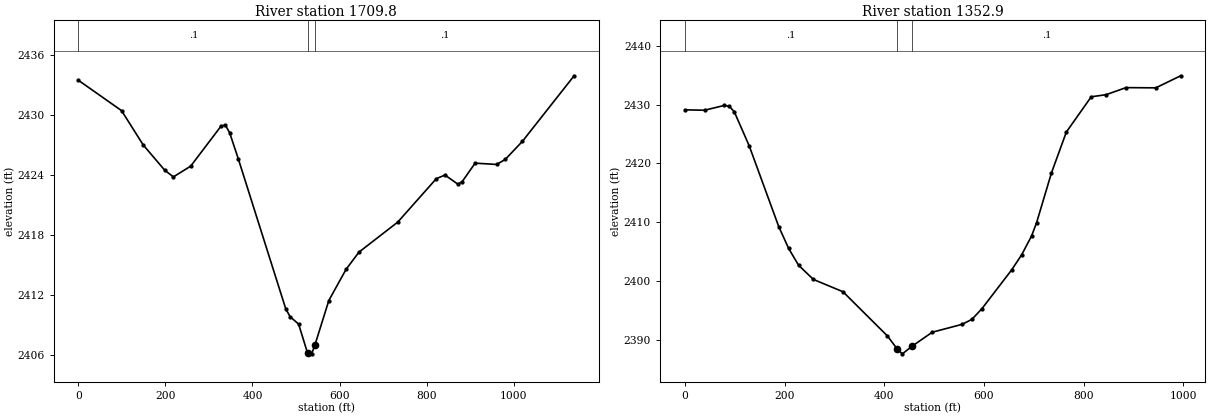
Type RM Length L Ch R = 1 ,1709.8  ,374,356.8,344.4
XS GIS Cut Line= 3
       2010159.1      310872.987     2009638.369      310999.633
     2009078.558      311223.848
#Sta/Elev= 30
       0 2433.43    99.2  2430.4   148.9 2426.98   198.5 2424.45   218.3 2423.79
     258 2424.86   327.5 2428.84   337.4 2428.98   347.4 2428.21   367.2 2425.62
   476.4 2410.63   486.3 2409.85   506.1 2409.09     526 2406.28   528.42406.244
   535.9 2406.13   543.42407.001   575.4 2411.45     615 2414.56   644.7 2416.28
   733.6 2419.27   822.6 2423.62   842.4 2423.97     872 2423.06   881.9 2423.32
   911.6 2425.16     961 2425.03   980.8 2425.53  1020.3 2427.34    1139 2433.88
#Mann= 3 , 0 , 0
       0      .1       0   528.4    .045       0   543.4      .1       0
Bank Sta=528.4,543.4
XS Rating Curve= 0 ,0
Exp/Cntr=0.3,0.1

Type RM Length L Ch R = 1 ,1352.9  ,111.6,116.3,121.8
XS GIS Cut Line= 3
     2009803.984      310608.198     2009427.271      310732.091
     2008964.942      311111.825
#Sta/Elev= 30
       0  2429.1    39.7 2429.04    79.3 2429.86    89.2  2429.7    99.1 2428.77
   128.9 2423.01   188.4 2409.24   208.2 2405.55     228 2402.71   257.8 2400.29
   317.2  2398.2   406.5 2390.68   426.5 2388.42   436.4 2387.65   456.4 2388.98
   496.3 2391.32   556.1 2392.66     576 2393.51     596 2395.32   655.8 2401.92
   675.8 2404.48   695.7 2407.68   705.7 2409.92   735.6  2418.4   765.5 2425.34
   815.4 2431.32   845.3 2431.68   885.2 2432.88     945 2432.84   994.8 2434.89
#Mann= 3 , 0 , 0
       0      .1       0   426.5    .045       0   456.4      .1       0
Bank Sta=426.5,456.4
XS Rating Curve= 0 ,-1
Exp/Cntr=0.3,0.1