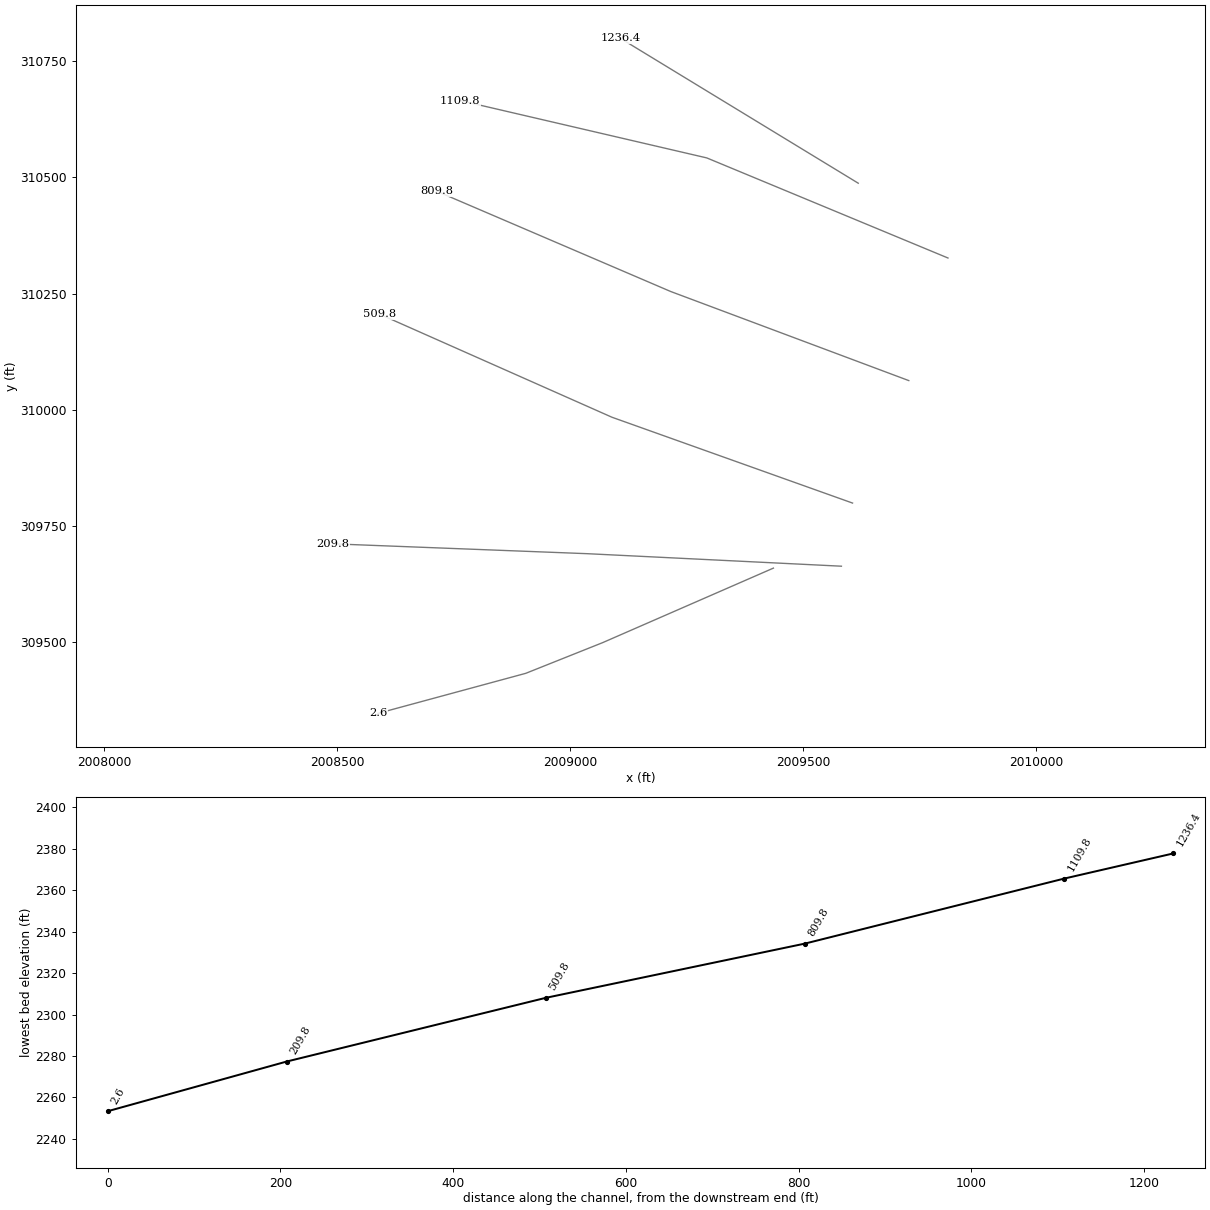
HEC-RAS study MeadowCrk.prj: MeadowCrk

--- MeadowCrk.g01 (geometry) --- (continued)

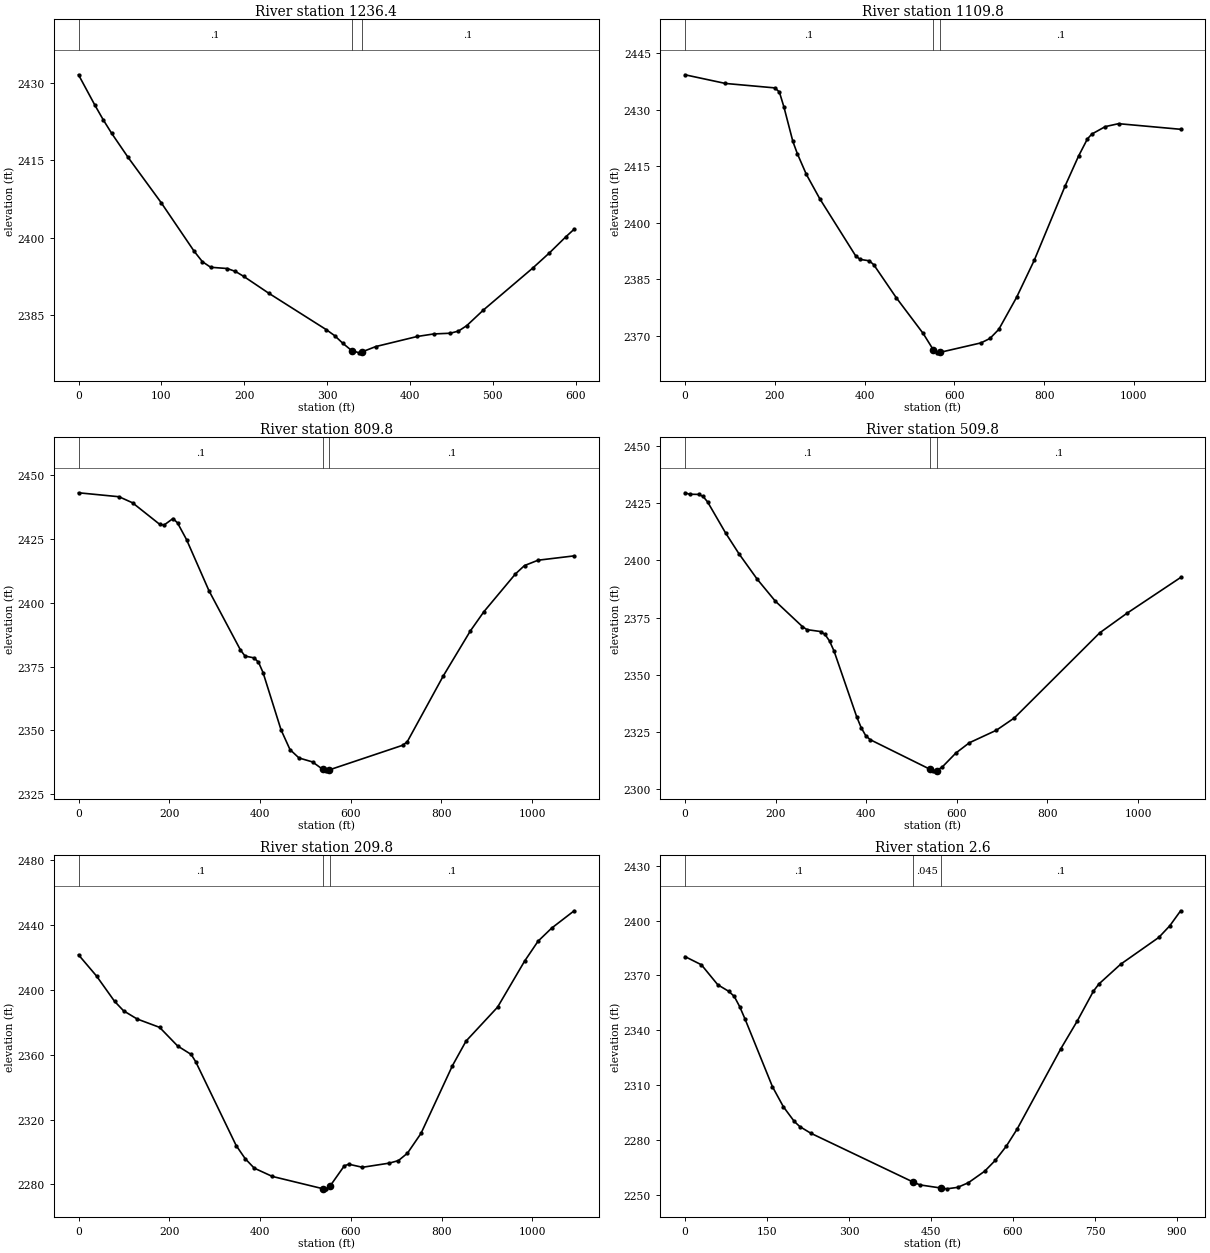
Type RM Length L Ch R = 1 ,1236.4  ,120.4,126.7,139.6
XS GIS Cut Line= 2
     2009617.894      310487.265     2009107.405      310798.884
#Sta/Elev= 30
       0 2431.54    19.9 2425.61    29.9  2422.8    39.9 2420.22    59.8 2415.54
    99.7 2406.77   139.6 2397.33   149.5 2395.32   159.5 2394.24   179.4    2394
   189.4 2393.43   199.4 2392.47   229.3 2389.24     299 2382.15     309    2381
     319  2379.5   329.72378.088   338.9 2377.66   341.72377.817   358.8 2378.88
   408.7 2380.83   428.6 2381.32   448.6 2381.46   458.5 2381.88   468.5 2382.93
   488.4 2385.93   548.2  2394.1   568.2 2397.02   588.1 2400.15   598.1 2401.62
#Mann= 3 , 0 , 0
       0      .1       0   329.7    .045       0   341.7      .1       0
Bank Sta=329.7,341.7
XS Rating Curve= 0 ,0
Exp/Cntr=0.3,0.1

Type RM Length L Ch R = 1 ,1109.8  ,298.6,300,292.8
XS GIS Cut Line= 3
     2009810.444      310326.402     2009292.799      310541.682
     2008763.602      310665.074
#Sta/Elev= 30
       0 2439.25    90.1 2436.95   200.2 2435.77   210.2 2434.69   220.2 2430.79
   240.3 2421.57   250.3 2418.32   270.3 2412.84   300.3 2406.36   380.4 2391.18
   390.4 2390.28   410.5 2389.91   420.5 2388.87   470.5 2380.14   530.6 2370.63
   553.1 2366.31   560.6  2365.5   568.12365.629   659.4 2368.14   679.2 2369.31
   698.9 2371.71   738.5 2380.19     778 2390.06   847.1 2409.87   876.8 2417.73
   896.5 2422.27   906.4 2423.54   936.1  2425.5   965.7 2426.28    1104 2424.79
#Mann= 3 , 0 , 0
       0      .1       0   553.1    .045       0   568.1      .1       0
Bank Sta=553.1,568.1
XS Rating Curve= 0 ,0
Exp/Cntr=0.3,0.1

Type RM Length L Ch R = 1 ,809.8   ,299.4,300,299.5
XS GIS Cut Line= 3
      2009726.37      310062.721     2009215.325      310254.362
     2008712.578       310470.29
#Sta/Elev= 30
       0 2443.08    89.3 2441.53   119.1 2439.16   178.6 2430.78   188.6 2430.43
   208.4    2433   218.3 2431.29   238.2 2424.75   287.8 2404.68   357.2 2381.49
   367.2 2379.13     387 2378.42   396.9 2376.72   406.9 2372.68   446.6 2350.24
   466.4 2342.49   486.2 2339.22     516 2337.67   538.32334.794   545.8 2334.18
   553.32334.574   714.9  2344.2   724.9 2345.56   804.4 2371.36   864.1 2388.98
     894 2396.52   963.6 2411.32   983.5 2414.58  1013.4 2416.67    1093 2418.37
#Mann= 3 , 0 , 0
       0      .1       0   538.3    .045       0   553.3      .1       0
Bank Sta=538.3,553.3
XS Rating Curve= 0 ,0
Exp/Cntr=0.3,0.1

Type RM Length L Ch R = 1 ,509.8   ,288.2,300,315.2
XS GIS Cut Line= 3
     2009605.643      309799.309     2009089.362      309983.877
     2008590.789      310205.466
#Sta/Elev= 30
       0 2429.58      10 2428.94    29.9 2428.87    39.9 2427.99    49.8 2425.62
    89.7 2411.99   119.6 2402.79   159.5 2391.78   199.4  2382.2   259.2 2371.08
   269.2 2369.76   299.1 2368.93     309 2367.66     319  2364.8     329 2360.39
   378.8 2331.76   388.8 2326.93   398.8 2323.44   408.7 2321.66   540.82308.712
   548.3 2308.03   555.82308.166   568.1 2309.77   597.9 2315.82   627.6  2320.3
   687.2 2325.77   726.8 2331.14   915.3 2368.35   974.8 2376.83  1093.9 2392.55
#Mann= 3 , 0 , 0
       0      .1       0   540.8    .045       0   555.8      .1       0
Bank Sta=540.8,555.8
XS Rating Curve= 0 ,0
Exp/Cntr=0.3,0.1

Type RM Length L Ch R = 1 ,209.8   ,189,207.2,225
XS GIS Cut Line= 3
     2009581.761       309663.52     2009036.328       309690.43
      2008490.77      309711.628
#Sta/Elev= 30
       0 2421.73    39.7 2408.65    79.4 2393.05    99.3 2387.18   129.1 2382.14
   178.7 2376.96   218.4 2365.48   248.2 2360.26   258.2 2355.78   347.5 2303.97
   367.4 2295.88   387.2 2290.09     427 2284.98   538.62277.381   546.1 2277.32
   553.6 2278.79   585.8 2291.57   595.7 2292.51   625.5 2290.62   685.1  2293.2
   704.9 2294.76   724.8 2299.32   754.6 2311.52     824 2353.38   853.8 2368.48
   923.3 2389.43   982.9 2417.85  1012.6 2430.16  1042.4 2438.19  1092.1 2448.91
#Mann= 3 , 0 , 0
       0      .1       0   538.6    .045       0   553.6      .1       0
Bank Sta=538.6,553.6
XS Rating Curve= 0 ,0
Exp/Cntr=0.3,0.1

Type RM Length L Ch R = 1 ,2.6     ,20.2,2.5,0
XS GIS Cut Line= 4
     2009435.801      309659.417     2009069.398      309499.166
     2008904.315      309433.133     2008587.035      309346.968
#Sta/Elev= 30
       0 2380.33      30 2375.85      60 2364.92      80 2361.34      90 2358.61
     100    2353     110 2346.08     160 2309.19     180 2298.22     200 2290.18
     210  2287.4     230 2283.79   417.5 2257.05   429.6 2255.53   467.5 2253.84
   478.9 2253.37   498.7 2254.18   518.4 2256.73   548.1    2263   567.8 2269.02
   587.7  2276.7   607.6  2286.1   687.3 2329.91   717.2 2344.99   747.1 2361.46
     757 2365.34   796.9 2376.17   866.6  2390.8   886.6 2397.13   906.5 2405.36
#Mann= 3 , 0 , 0
       0      .1       0   417.5    .045       0   467.5      .1       0
Bank Sta=417.5,467.5
XS Rating Curve= 0 ,0
Exp/Cntr=0.3,0.1

Chan Stop Cuts=-1
Use User Specified Reach Order=0
Composite Channel Slope=5